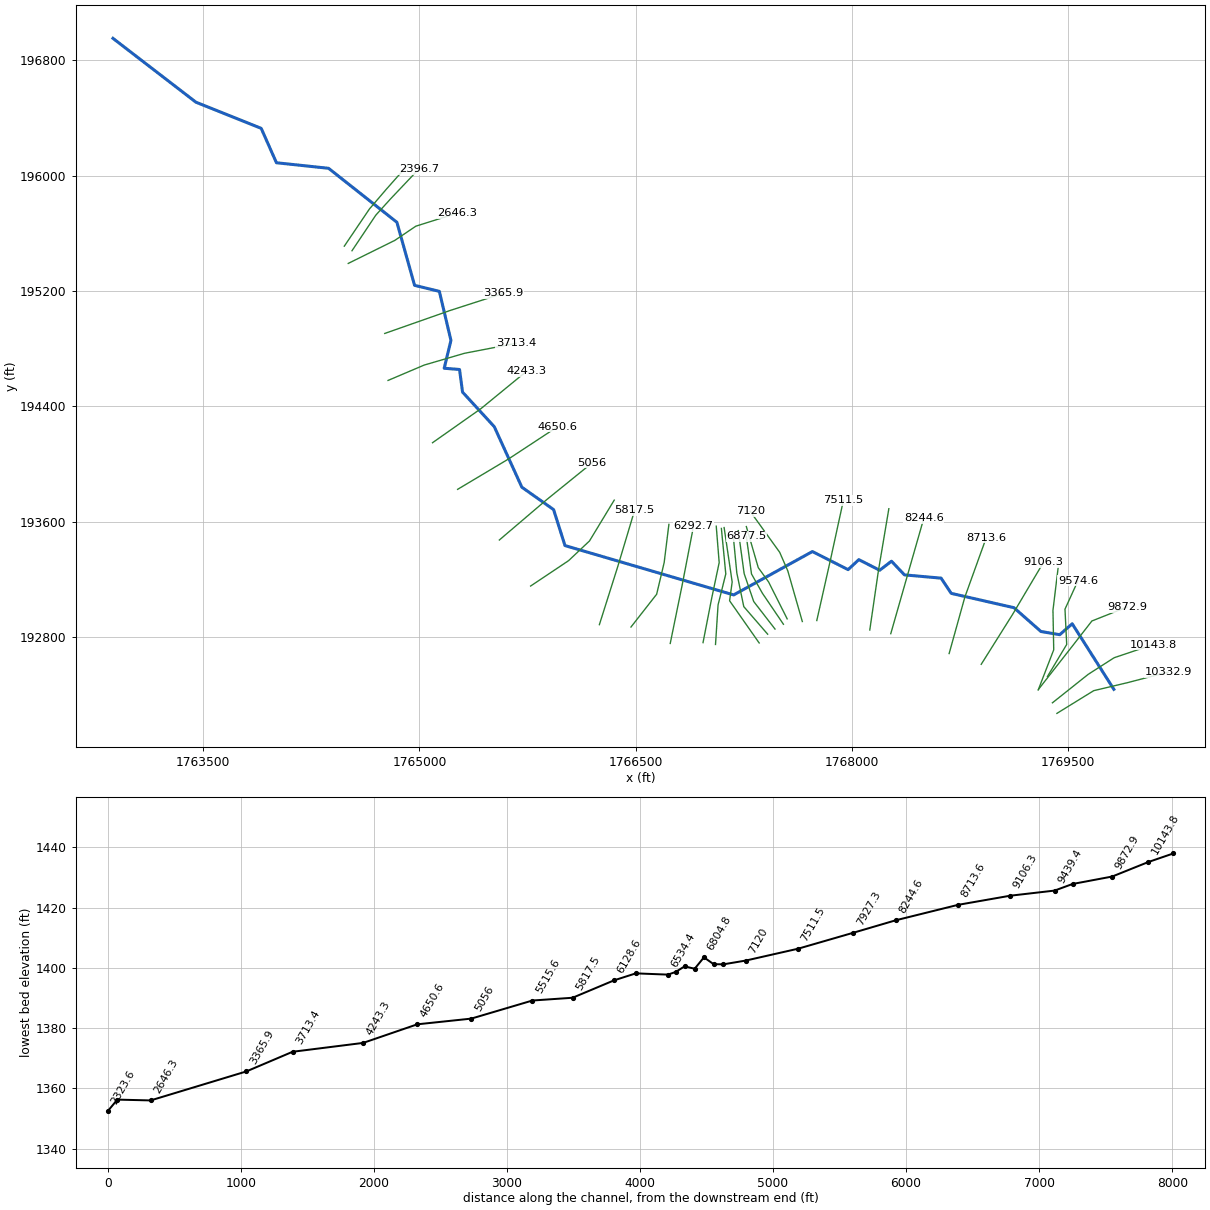
--- LtleHufCr.prj (project) ---

Proj Title=LtleHufCr
Current Plan=p01
Default Exp/Contr=0,0
English Units
Geom File=g01
Flow File=f01
Plan File=p01
BEGIN DESCRIPTION:
END DESCRIPTION:
DSS Export Rating Curves= 0
DSS Export Rating Curve Sorted= 0
DSS Export Volume Flow Curves= 0
DXF OffsetX= 0
DXF OffsetY= 0
DXF ScaleX= 0
DXF ScaleY= 0

--- LtleHufCr.p01 (plan) ---

Plan Title=Floodplain
Program Version=4.00
Geom File=g01
Flow File=f01
K Sum by GR=0
Std Step Tol=0.01
Critical Tol=0.01
Num of Std Step Trials=20
Max Error Tol=0.3
Flow Tol Ratio=0.001
Split Flow NTrial=30
Split Flow Tol=0.02
Split Flow Ratio=0.02
Log Output Level=0
Friction Slope Method=1
Unsteady Friction Slope Method=2
Unsteady Bridges Friction Slope Method=1
Global Log Level=0
CheckData=False
Run HTab=0
Run UNet=0
Run PostProcess=0
UNET Theta=0
UNET Theta Warmup=0
UNET ZTol=0
UNET ZSATol=0
UNET MxIter=0
UNET MaxInSteps=0
UNET DtIC=0
UNET DtMin=0
UNET MaxCRTS=0
UNET WFStab=0
UNET SFStab=0
UNET WFX=0
UNET SFX=0
UNET DSS MLevel=0
UNET DZMax Abort=0
UNET Convert EG Bridges=0
UNET Use Existing IB Tables=0
UNET Froude Limit=0
UNET Froude Power=0
Write IC File=0
Echo Input=False
Echo Output=False
Write Detailed=0

--- LtleHufCr.f01 (steady flow) ---

Flow Title=NFF Regression Equation
Program Version=4.00
Number of Profiles=1
Profile Names=P100yr
River Rch & RM=LtleHufCr,Main      ,10332.9
553.2813
River Rch & RM=LtleHufCr,Main      ,9872.9
571.1730
River Rch & RM=LtleHufCr,Main      ,9439.4
722.0478
River Rch & RM=LtleHufCr,Main      ,8244.6
755.4429
River Rch & RM=LtleHufCr,Main      ,7927.3
828.4366
River Rch & RM=LtleHufCr,Main      ,5817.5
864.7729
River Rch & RM=LtleHufCr,Main      ,5515.6
988.2262
River Rch & RM=LtleHufCr,Main      ,3365.9
1020.906
River Rch & RM=LtleHufCr,Main      ,2646.3
1141.506
River Rch & RM=LtleHufCr,Main      ,907.9
1214.717
River Rch & RM=LtleHufCr,Main      ,519.3
1220.268
Boundary for River Rch & Prof#=LtleHufCr,Main      ,1
Up Type=0
Dn Type=3
Dn Slope=0.021631

--- LtleHufCr.g01 (geometry) ---

Geom Title=USGS 10m DEM
Program Version=4.00

River Reach=LtleHufCr       ,Main
Reach XY= 30
     1769817.574      192435.934     1769528.691      192890.627
     1769442.041       192814.86     1769311.856      192837.046
     1769124.659      193002.031     1768689.398      193101.601
     1768619.073      193207.089     1768364.879      193229.828
     1768274.984      193324.715     1768192.938      193261.925
     1768048.417      193335.543      1767974.01      193266.111
     1767726.199      193391.691     1767180.194      193090.695
     1766009.832      193433.073     1765930.717      193682.696
     1765710.421      193838.199     1765519.453      194257.646
     1765299.158      194497.721     1765278.225      194654.608
     1765171.901      194663.398     1765218.678      194856.468
     1765138.199      195196.801     1764966.328      195238.404
     1764843.718      195675.992     1764369.639      196050.459
     1764008.077      196088.895     1763902.362      196327.605
     1763449.495      196509.025     1762873.792      196952.068

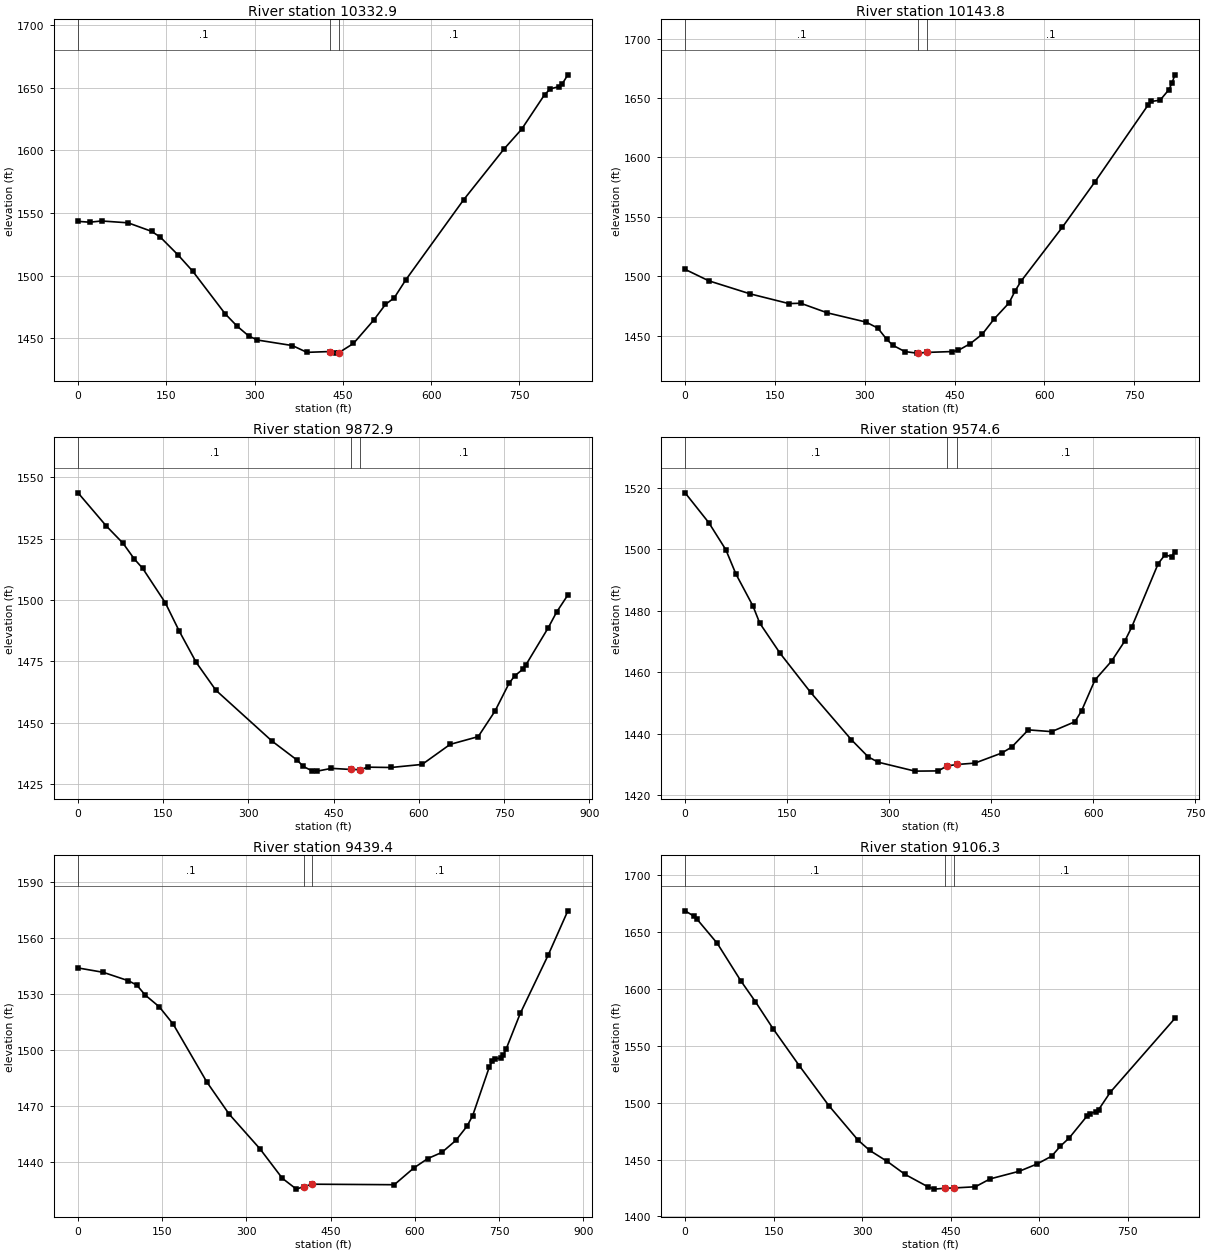
Type RM Length L Ch R = 1 ,10332.9 ,179.4,189.2,197.1
XS GIS Cut Line= 4
     1769422.612       192268.98      1769677.85      192426.474
     1769913.561       192482.33     1770194.219      192555.565
#Sta/Elev= 30
       0 1543.27      20  1542.6      40 1543.59      85 1542.11     125  1535.3
     140  1530.6     170 1516.42     195 1503.39   249.9 1469.48   269.9 1459.74
   289.9 1451.78   304.9 1448.48   364.2 1444.07   388.9 1438.65   428.2 1439.31
   438.3 1438.03   443.2 1438.41     468 1445.76   502.6 1464.52   522.4 1476.96
   537.2 1482.15   556.9 1496.56   655.2 1560.54   724.1 1601.25   753.6 1616.81
   792.9  1644.6   802.7 1649.12   817.5 1650.96   822.4 1652.83   832.2 1660.32
#Mann= 3 , 0 , 0
       0      .1       0   428.2    .045       0   443.2      .1       0
Bank Sta=428.2,443.2
XS Rating Curve= 0 ,0
Exp/Cntr=0.3,0.1

Type RM Length L Ch R = 1 ,10143.8 ,277.1,270.9,277.3
XS GIS Cut Line= 4
     1769391.469      192342.245     1769639.345      192539.583
     1769819.837      192655.098     1770091.778      192746.547
#Sta/Elev= 30
       0  1505.7    39.6 1496.05   108.9 1485.03   173.3 1476.89   193.1 1477.16
   237.6 1469.07     302 1461.33   321.8 1456.26   336.8 1446.72   346.7 1441.86
   366.7 1436.52   386.6 1435.16   388.9 1435.22   403.9 1435.77   446.4 1436.49
   456.4 1437.53   476.3 1443.16   496.2 1451.05   516.2 1463.98     541 1477.44
   550.9 1487.34   560.8 1495.58   630.1 1541.24   684.5 1579.41   773.5 1644.31
   778.5  1647.1   793.3 1648.17   808.1 1657.11   813.1 1662.59     818 1669.52
#Mann= 3 , 0 , 0
       0      .1       0   388.9    .045       0   403.9      .1       0
Bank Sta=388.9,403.9
XS Rating Curve= 0 ,0
Exp/Cntr=0.3,0.1

Type RM Length L Ch R = 1 ,9872.9  ,132.6,298.3,189.6
XS GIS Cut Line= 4
     1769295.388      192436.563     1769530.495      192736.706
     1769665.262      192909.979     1769908.325      193006.241
#Sta/Elev= 30
       0 1543.66    49.5 1530.22    79.2 1523.13      99 1516.74   113.9 1512.88
   153.5 1498.95   178.2 1487.34     208 1474.63   242.6  1463.3   341.6 1442.56
   386.2 1434.74   396.2  1432.3   411.2 1430.55   421.2 1430.35   446.1 1431.48
   480.6 1431.02   495.6 1430.97     511 1431.96   550.9 1431.83   605.7 1433.08
     655 1441.24   704.4 1444.39     734 1454.79   758.6 1466.04   768.5 1469.09
   783.3 1471.89   788.2 1473.53   827.7 1488.71   842.5 1495.12   862.2 1502.04
#Mann= 3 , 0 , 0
       0      .1       0   480.6    .045       0   495.6      .1       0
Bank Sta=480.6,495.6
XS Rating Curve= 0 ,0
Exp/Cntr=0.3,0.1

Type RM Length L Ch R = 1 ,9574.6  ,104.9,135.2,142.3
XS GIS Cut Line= 4
     1769356.795      192524.725     1769490.499      192747.123
     1769478.585      192992.027     1769568.189      193188.156
#Sta/Elev= 30
       0 1518.34    34.9 1508.62    59.9 1499.84    74.8 1491.92    99.8 1481.54
   109.8 1475.97   139.7 1466.17   184.6 1453.47   244.5 1438.08   269.3  1432.5
     284 1430.77     338 1427.87   372.3 1427.94   385.2 1429.57   400.2 1430.03
   426.2 1430.48   465.5 1433.74   480.2 1435.66   504.7 1441.28     539 1440.71
   573.3 1443.93   583.1 1447.51   602.7 1457.48   627.2 1463.65   646.8 1470.23
   656.6 1474.59   695.8 1495.36   705.6 1498.14   715.4 1497.64   720.3 1499.25
#Mann= 3 , 0 , 0
       0      .1       0   385.2    .045       0   400.2      .1       0
Bank Sta=385.2,400.2
XS Rating Curve= 0 ,0
Exp/Cntr=0.3,0.1

Type RM Length L Ch R = 1 ,9439.4  ,370.3,333.1,324.5
XS GIS Cut Line= 4
     1769292.765       192430.96      1769400.48      192710.057
     1769395.185      192984.084     1769431.192       193281.09
#Sta/Elev= 30
       0 1544.06    44.9 1541.72    89.8  1537.2   104.7 1534.88   119.7 1529.54
   144.6 1523.28   169.5 1513.98   229.4 1483.02   269.2  1465.8   324.1 1447.23
   363.9 1431.47   388.9 1425.68   402.1 1427.05   417.1 1428.32   563.3 1428.04
   598.2 1437.03   623.1 1442.06     648 1445.33     673 1451.76   692.9  1459.4
   702.9 1465.01   732.8 1491.25   737.8 1494.11   742.8  1495.4   752.8 1495.84
   757.7 1497.64   762.7  1500.8   787.6 1519.68   837.5    1551   872.4 1574.63
#Mann= 3 , 0 , 0
       0      .1       0   402.1    .045       0   417.1      .1       0
Bank Sta=402.1,417.1
XS Rating Curve= 0 ,0
Exp/Cntr=0.3,0.1

Type RM Length L Ch R = 1 ,9106.3  ,386.8,392.7,394.5
XS GIS Cut Line= 3
     1768897.443      192609.327     1769114.115      192954.035
     1769329.647      193317.309
#Sta/Elev= 30
       0 1668.75    14.9 1664.05    19.9 1661.56    54.6 1640.07    94.3 1607.24
   119.2 1588.73     149 1565.06   193.6 1532.39   243.3 1497.52     293 1467.02
   312.8 1457.98   342.6 1448.28   372.4 1436.99   412.1  1425.8   422.1 1423.98
   440.3 1424.77   455.3 1425.01   491.6 1426.05   516.5 1432.96   566.2 1439.74
     596 1446.07   620.8 1452.96   635.7  1461.8   650.6    1469   680.5  1488.1
   685.4 1490.46   695.4 1491.94   700.3  1493.8   720.2 1509.22   829.6 1574.16
#Mann= 3 , 0 , 0
       0      .1       0   440.3    .045       0   455.3      .1       0
Bank Sta=440.3,455.3
XS Rating Curve= 0 ,0
Exp/Cntr=0.3,0.1

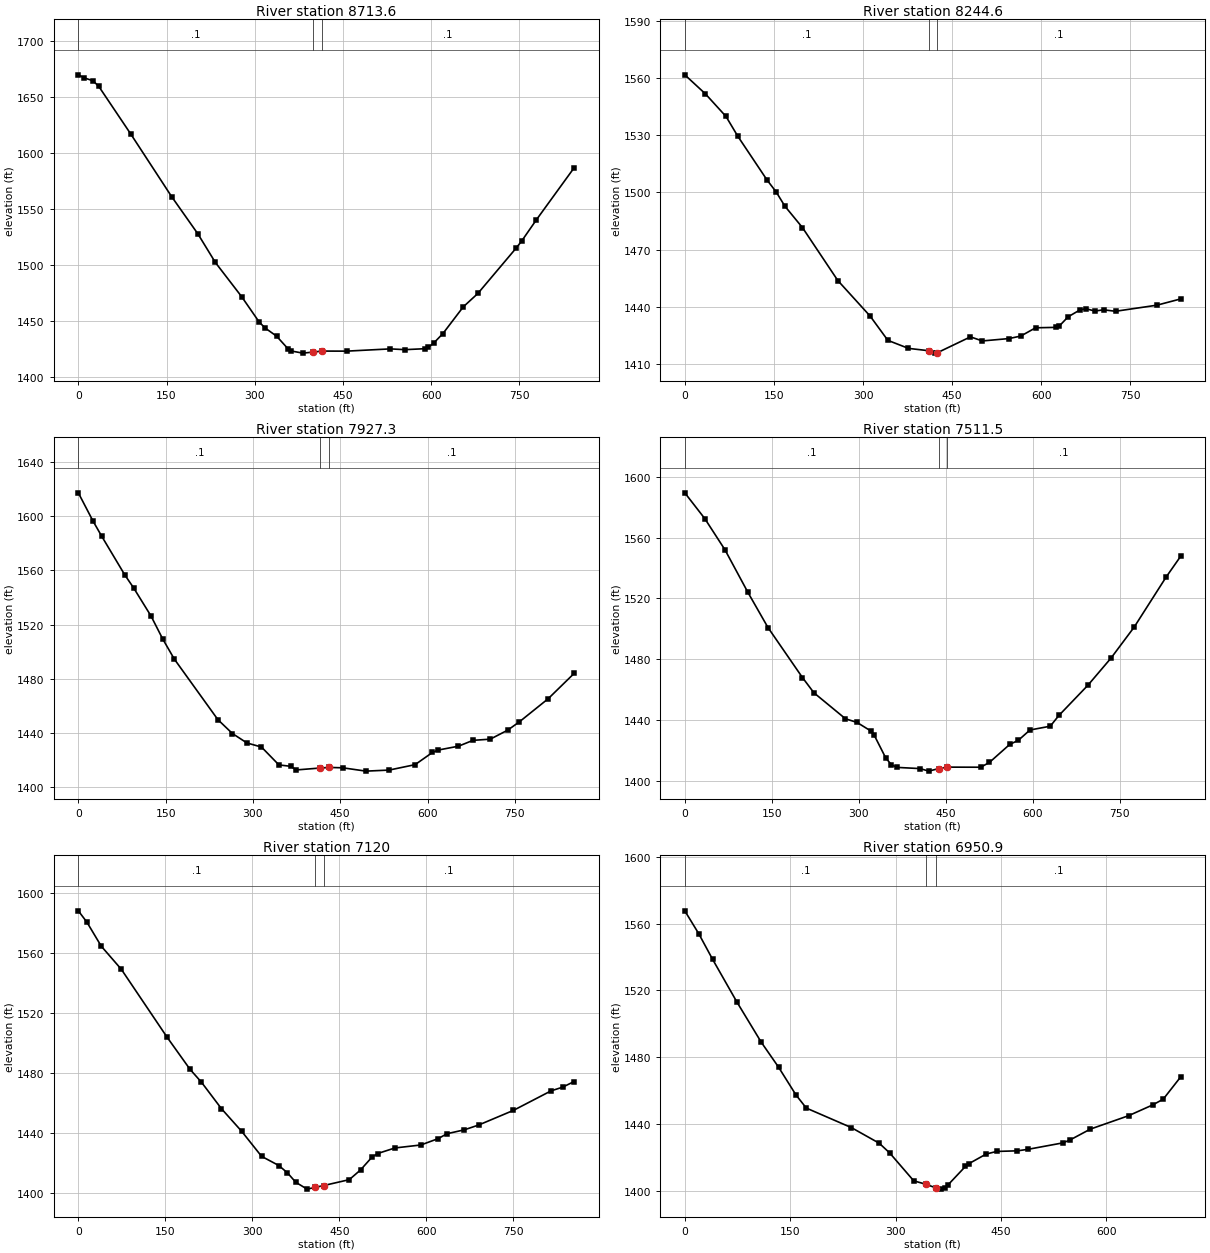
Type RM Length L Ch R = 1 ,8713.6  ,469.4,469,470.2
XS GIS Cut Line= 3
     1768674.884      192684.042     1768783.914      193075.817
     1768932.027      193486.694
#Sta/Elev= 30
       0 1670.15     9.9 1667.42    24.8 1664.88    34.7 1659.85    89.3 1617.05
   158.7 1561.09   203.3 1527.77   233.1 1502.12   277.7 1471.57   307.5 1448.89
   317.4 1443.57   337.2 1436.14   357.1 1424.58     362 1422.87   381.9 1420.94
   399.2 1421.85   414.2 1422.78   456.3 1422.72   530.7 1424.74   555.6 1424.05
   590.3 1424.92   595.3 1426.07   605.2 1430.34   620.1 1438.41   654.8 1462.38
   679.6 1474.36   744.2 1514.68   754.1 1521.31   778.9 1540.15   843.4 1586.95
#Mann= 3 , 0 , 0
       0      .1       0   399.2    .045       0   414.2      .1       0
Bank Sta=399.2,414.2
XS Rating Curve= 0 ,0
Exp/Cntr=0.3,0.1

Type RM Length L Ch R = 1 ,8244.6  ,303.2,317.3,310.9
XS GIS Cut Line= 3
     1768269.991      192821.929     1768385.779      193226.744
     1768499.756      193624.412
#Sta/Elev= 30
       0 1561.55    34.7 1551.58    69.4 1539.73    89.2  1529.4   138.7 1506.35
   153.6 1500.33   168.4  1492.8   198.1 1481.53   257.6 1453.82   312.1 1435.16
   341.8  1422.5   376.5 1418.29   410.4 1417.07     421  1415.8   425.4 1416.05
   480.9 1424.32   500.8 1422.18   545.6 1423.42   565.6 1424.74   590.5 1429.06
   625.4  1429.3   630.4 1429.99   645.3 1434.82   665.3 1438.44   675.2 1439.07
   690.2 1437.84   705.1 1438.48   725.1 1437.72   794.8 1440.91   834.7 1444.18
#Mann= 3 , 0 , 0
       0      .1       0   410.4    .045       0   425.4      .1       0
Bank Sta=410.4,425.4
XS Rating Curve= 0 ,0
Exp/Cntr=0.3,0.1

Type RM Length L Ch R = 1 ,7927.3  ,420.1,415.8,412.2
XS GIS Cut Line= 3
     1768124.351      192847.202     1768184.029      193257.467
     1768256.591      193688.719
#Sta/Elev= 30
       0 1617.42      25 1596.72      40 1585.44    79.9 1556.68    94.9 1547.21
   124.9 1526.34   144.8 1509.53   164.8 1494.58   239.8 1449.73   264.7 1439.49
   289.7  1432.5   314.7 1429.48   344.6 1416.28   364.6 1415.25   374.6 1412.56
   415.9 1413.99   430.9 1414.41   454.3 1414.14   494.1 1411.68   533.8 1412.44
   578.6 1416.47   608.4 1425.47   618.3 1427.26   653.1 1430.11     678 1434.42
   707.8 1435.32   737.6 1441.95   757.5 1448.02   807.2 1465.18   851.9 1483.95
#Mann= 3 , 0 , 0
       0      .1       0   415.9    .045       0   430.9      .1       0
Bank Sta=415.9,430.9
XS Rating Curve= 0 ,0
Exp/Cntr=0.3,0.1

Type RM Length L Ch R = 1 ,7511.5  ,373.9,391.5,405.8
XS GIS Cut Line= 3
     1767756.751      192912.987     1767854.457      193347.321
     1767941.437      193747.448
#Sta/Elev= 30
       0 1589.54    34.6  1572.5    69.2 1552.08   108.8 1524.01   143.4 1500.87
   202.8 1467.96   222.6 1457.92     277 1440.82   296.8 1438.44   321.5 1432.61
   326.5 1430.03   346.3 1415.11   356.2 1410.53     366 1408.82   405.6 1408.04
   420.5 1406.37   437.7 1408.05   452.7    1409   510.1 1408.94   525.1 1412.09
     560 1423.92     575 1426.67     595 1433.44     630 1435.94   644.9 1443.02
   694.9 1462.91   734.8 1480.81   774.8 1501.26   829.7  1534.1   854.7 1547.74
#Mann= 3 , 0 , 0
       0      .1       0   437.7    .045       0   452.7      .1       0
Bank Sta=437.7,452.7
XS Rating Curve= 0 ,0
Exp/Cntr=0.3,0.1

Type RM Length L Ch R = 1 ,7120    ,163.9,169.1,174.5
XS GIS Cut Line= 4
     1767656.339      192906.115     1767555.665       193257.38
     1767499.403      193386.313     1767295.459      193669.558
#Sta/Elev= 30
       0 1588.34    14.8 1580.75    39.5 1564.74    74.1 1549.31   153.1  1503.9
   192.6 1482.49   212.3 1473.88   246.9 1456.14   281.5 1441.16     316 1424.36
   345.7 1418.23   360.5 1413.38   375.1 1407.01   394.5 1402.45   408.2  1403.6
   423.2 1404.85   467.3 1408.78   486.7 1415.27   506.1 1423.68     516  1426.2
     546 1429.95   590.8 1431.94   620.8 1436.22   635.7 1439.45   665.6 1442.05
   690.6  1445.3   750.4 1455.06   815.2 1468.07   835.2 1470.56   855.1 1474.32
#Mann= 3 , 0 , 0
       0      .1       0   408.2    .045       0   423.2      .1       0
Bank Sta=408.2,423.2
XS Rating Curve= 0 ,0
Exp/Cntr=0.3,0.1

Type RM Length L Ch R = 1 ,6950.9  ,76.4,73.4,70.4
XS GIS Cut Line= 4
     1767551.213      192924.757     1767422.411       193180.73
     1767350.673      193280.185     1767268.083      193564.844
#Sta/Elev= 30
       0 1567.64    19.8    1554    39.5 1538.68    74.1 1513.14   108.7 1489.12
   133.4 1474.15   158.1 1457.59   172.9 1449.67   237.2 1437.96   276.7 1428.64
   291.5 1422.86   325.8 1406.15   343.1 1404.11   358.1 1401.81     365 1401.19
   369.9 1401.98   374.8 1403.82   399.4 1414.79   404.3 1416.42   428.9 1422.18
   443.8 1423.73   473.4  1424.1   488.2 1424.98   537.6 1428.82   547.5 1430.43
   577.1 1437.08   631.5  1445.1   666.1  1451.6   680.9 1455.02   705.6 1468.26
#Mann= 3 , 0 , 0
       0      .1       0   343.1    .045       0   358.1      .1       0
Bank Sta=343.1,358.1
XS Rating Curve= 0 ,0
Exp/Cntr=0.3,0.1

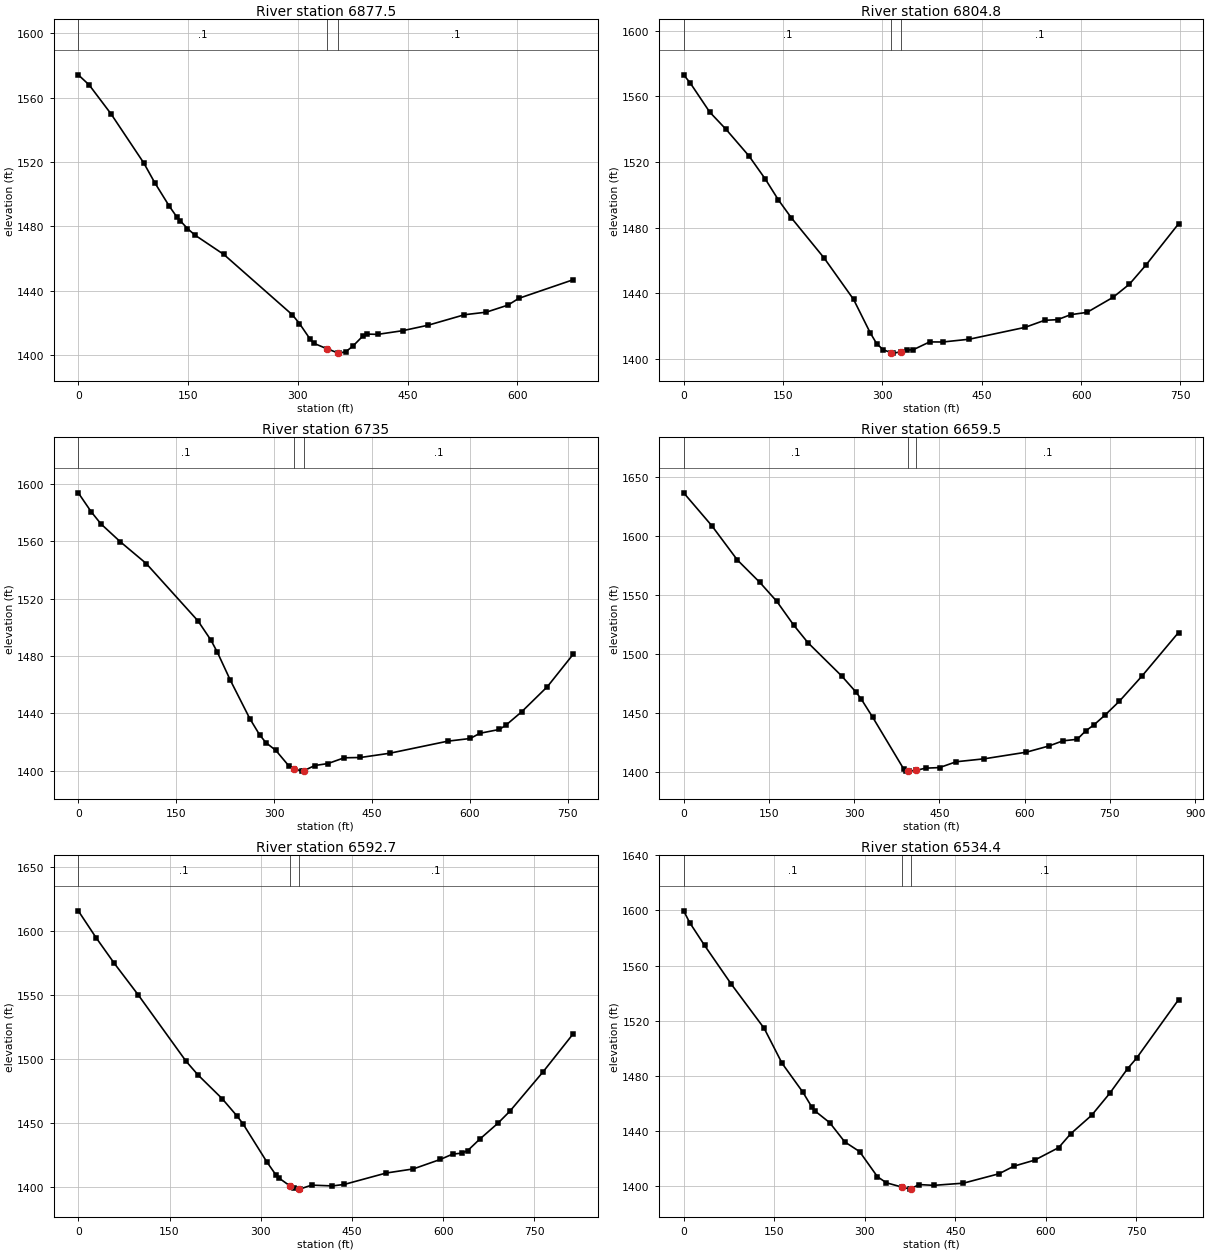
Type RM Length L Ch R = 1 ,6877.5  ,78.6,72.7,66.9
XS GIS Cut Line= 4
     1767525.381      192887.206     1767380.173      193101.197
     1767303.748      193236.215     1767268.083      193496.061
#Sta/Elev= 30
       0 1574.17    14.9 1567.87    44.8 1549.85    89.5 1519.37   104.4 1507.19
   124.3 1492.58   134.3 1486.05   139.2 1483.52   149.2 1478.65   159.1 1474.67
   198.9 1462.53   292.6 1424.98   302.2  1419.6   316.8 1409.88   321.6 1407.38
   339.8 1403.94   354.8 1401.36   355.6 1401.24   365.3 1402.08     375 1405.53
   389.5 1412.19   394.4 1413.08   408.9 1412.89   443.4  1415.2   478.1 1418.61
   527.6  1425.1   557.3 1426.68     587 1431.08   601.8 1435.28     676 1446.83
#Mann= 3 , 0 , 0
       0      .1       0   339.8    .045       0   354.8      .1       0
Bank Sta=339.8,354.8
XS Rating Curve= 0 ,0
Exp/Cntr=0.3,0.1

Type RM Length L Ch R = 1 ,6804.8  ,71,69.8,68.6
XS GIS Cut Line= 4
     1767466.789      192854.089     1767319.033      193045.152
     1767252.798      193238.762     1767212.038      193536.821
#Sta/Elev= 30
       0 1573.13     9.9 1568.17    39.4 1550.39    64.1 1539.85    98.6 1523.68
   123.2 1509.63     143 1496.89   162.7  1485.9     212  1461.5   256.5 1436.25
   281.5 1416.01   291.4 1409.23   301.4 1405.52   312.9 1403.87   316.4 1403.51
   327.9 1404.26   336.4 1405.42   346.3 1405.53   371.3 1410.34   391.3  1410.3
   431.2 1411.99   515.2  1419.2   544.8  1423.5   564.5 1423.91   584.2 1426.95
   608.9 1428.35   648.4 1437.58     673 1445.57   697.7 1457.12     747 1482.29
#Mann= 3 , 0 , 0
       0      .1       0   312.9    .045       0   327.9      .1       0
Bank Sta=312.9,327.9
XS Rating Curve= 0 ,0
Exp/Cntr=0.3,0.1

Type RM Length L Ch R = 1 ,6735    ,83.2,75.5,67.8
XS GIS Cut Line= 4
     1767415.838      192818.424      1767250.25      193009.487
     1767201.848      193243.858     1767176.372      193508.798
#Sta/Elev= 30
       0 1593.68    19.8 1580.47    34.7 1572.03    64.4 1559.57   104.1 1544.41
   183.4 1504.44   203.3    1491   213.2 1482.52     233 1463.09   262.8 1436.35
   277.8 1425.07   287.7 1419.49   302.7 1414.19   322.6  1403.4   330.6  1401.4
   342.6 1399.72   345.6 1400.01   362.5 1403.64   382.5 1404.98   407.4 1409.01
   432.3 1409.22   477.2 1412.18   566.1 1420.59   600.6 1422.46   615.4 1426.09
     645 1428.74   654.8 1431.56   679.4 1441.04   718.9 1458.62   758.3  1481.1
#Mann= 3 , 0 , 0
       0      .1       0   330.6    .045       0   345.6      .1       0
Bank Sta=330.6,345.6
XS Rating Curve= 0 ,0
Exp/Cntr=0.3,0.1

Type RM Length L Ch R = 1 ,6659.5  ,69.2,66.7,64.3
XS GIS Cut Line= 4
     1767357.013      192757.438     1767151.763      193050.298
     1767169.698       193180.73     1767113.853      193558.016
#Sta/Elev= 30
       0 1636.97    49.7 1608.92    94.4 1579.96   134.1 1560.84   163.9 1544.73
   193.7 1524.53   218.6 1509.68   278.2 1481.28     303 1467.79   312.9 1461.41
   332.8 1446.15   386.9 1402.55   391.8 1400.55   394.1 1400.53   396.6 1400.52
   409.1 1401.22   425.9 1403.05   450.3 1403.53   479.5 1408.48   528.9 1410.99
   603.2 1416.64   642.8  1421.9   667.6 1426.29   692.4 1427.54   707.2 1434.62
   722.1 1439.88   741.9 1448.35   766.7 1459.93   806.3 1481.22   870.7 1518.27
#Mann= 3 , 0 , 0
       0      .1       0   394.1    .045       0   409.1      .1       0
Bank Sta=394.1,409.1
XS Rating Curve= 0 ,0
Exp/Cntr=0.3,0.1

Type RM Length L Ch R = 1 ,6592.7  ,56.6,58.3,61.5
XS GIS Cut Line= 4
     1767054.092      192747.093     1767071.925      193022.224
     1767125.422      193236.215     1767094.852      193552.106
#Sta/Elev= 30
       0 1615.94    29.5 1594.81    59.1 1575.01    98.5 1550.35   177.2 1498.51
   196.9 1487.79   236.3 1469.42   260.9 1455.81   270.8 1449.68     310 1419.94
   324.7 1409.92   329.6 1407.44     348 1401.19   354.1 1399.49     363 1398.69
   363.9 1398.67   383.6 1401.79   417.9 1401.17   437.5 1402.36   506.2 1411.24
   550.8 1414.44   595.5  1421.9   615.3 1425.98   630.2 1426.75   640.1 1428.67
   659.9 1437.61   689.7 1450.01   709.5 1459.44   764.1 1490.18   813.6 1519.85
#Mann= 3 , 0 , 0
       0      .1       0     348    .045       0     363      .1       0
Bank Sta=348,363
XS Rating Curve= 0 ,0
Exp/Cntr=0.3,0.1

Type RM Length L Ch R = 1 ,6534.4  ,243.5,241.8,238.8
XS GIS Cut Line= 4
     1766967.477      192759.831      1767026.07      193060.437
     1767079.567      193315.188     1767059.187      193567.391
#Sta/Elev= 30
       0 1599.71     9.9 1591.22    34.6 1574.64      79 1546.44   133.4 1514.42
     163 1489.07   197.6 1468.03   212.4 1457.23   217.4 1454.52     242 1445.94
   266.8 1432.06   291.4    1425     321 1406.77   335.7 1402.38     361 1399.31
     375 1397.77     376 1397.96   389.8 1401.08   414.3 1400.51   463.4  1402.1
   522.4 1408.93   546.9 1414.42   581.4 1418.82   621.1 1427.87     641 1437.92
   675.7 1451.34   705.5 1467.19   735.2 1485.14   750.1 1492.77   819.6  1535.2
#Mann= 3 , 0 , 0
       0      .1       0     361    .045       0     376      .1       0
Bank Sta=361,376
XS Rating Curve= 0 ,0
Exp/Cntr=0.3,0.1

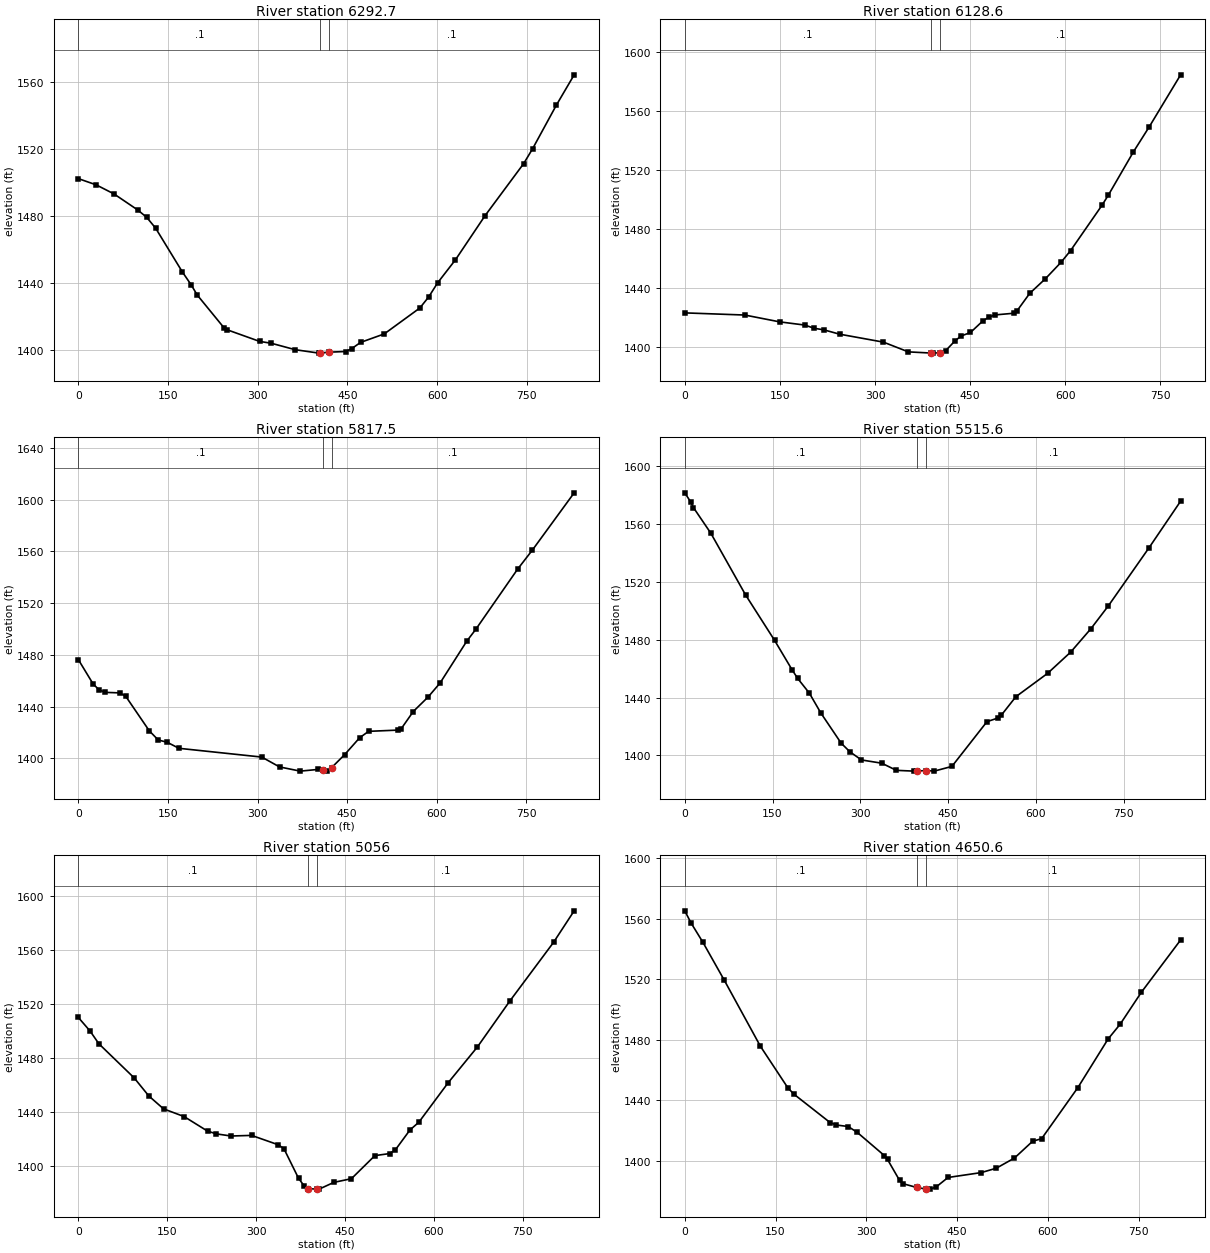
Type RM Length L Ch R = 1 ,6292.7  ,164.8,164.1,163.1
XS GIS Cut Line= 3
     1766739.938      192753.961     1766822.549      193158.006
      1766901.45       193567.33
#Sta/Elev= 30
       0 1502.52    29.8  1498.8    59.6 1493.38    99.4 1483.76   114.3 1479.39
   129.2 1472.94   173.9 1446.78   188.8 1438.98   198.8 1432.95   243.5  1413.4
   248.4 1412.21   303.1 1405.21     323 1404.07   362.7 1400.24   402.5 1398.19
   404.9 1398.28   419.9 1398.77   447.1 1399.16   457.1 1400.83     472 1404.59
   511.7 1409.68   571.2 1425.17   586.1 1431.83     601 1440.25   630.8 1454.01
   680.4 1480.43   744.9 1511.53   759.8 1520.38   799.5 1546.42   829.3 1564.57
#Mann= 3 , 0 , 0
       0      .1       0   404.9    .045       0   419.9      .1       0
Bank Sta=404.9,419.9
XS Rating Curve= 0 ,0
Exp/Cntr=0.3,0.1

Type RM Length L Ch R = 1 ,6128.6  ,312.6,311,309.7
XS GIS Cut Line= 4
     1766467.665      192868.055     1766645.757      193095.465
     1766697.814      193314.654     1766730.693      193580.422
#Sta/Elev= 30
       0 1423.11    94.6 1421.65   149.4 1417.04   189.2 1414.86   204.2 1412.66
   219.1 1411.65     244  1408.7   313.3  1403.3   352.5 1396.71   388.2 1395.91
   391.7 1395.86   403.2 1396.19   411.3 1397.49     426 1404.12   435.8 1407.47
   450.5 1409.83     470 1417.67   479.8 1420.32   489.6 1421.74   519.1 1422.88
     524 1424.55   543.9 1436.31   568.7 1446.24   593.5 1457.43   608.4 1465.31
     658 1496.03   667.9 1502.82   707.5 1532.17   732.3 1549.02   781.9 1584.29
#Mann= 3 , 0 , 0
       0      .1       0   388.2    .045       0   403.2      .1       0
Bank Sta=388.2,403.2
XS Rating Curve= 0 ,0
Exp/Cntr=0.3,0.1

Type RM Length L Ch R = 1 ,5817.5  ,328.1,301.9,289.6
XS GIS Cut Line= 3
     1766248.476      192884.495     1766375.495       193285.94
     1766492.836      193677.646
#Sta/Elev= 30
       0 1476.31    24.8 1457.43    34.7 1452.95    44.6 1450.98    69.4 1450.57
    79.3 1447.97   118.9 1421.17   133.8 1414.15   148.6 1412.44   168.4 1407.73
   307.1 1400.95   336.8 1393.34   371.5 1390.09   401.2  1391.4   408.8 1390.81
   416.1 1390.11   423.8 1392.71     446 1402.93   470.9 1415.88   485.9 1420.85
   535.8 1421.82   540.7    1423   560.7 1436.18   585.6 1447.43   605.6 1458.25
   650.4 1490.67   665.4 1499.73   735.2 1546.13   760.2 1561.05     830 1605.22
#Mann= 3 , 0 , 0
       0      .1       0   408.8    .045       0   423.8      .1       0
Bank Sta=408.8,423.8
XS Rating Curve= 0 ,0
Exp/Cntr=0.3,0.1

Type RM Length L Ch R = 1 ,5515.6  ,459.8,459.6,460.4
XS GIS Cut Line= 4
     1765771.412      193152.396     1766034.766      193328.354
     1766179.979      193465.347     1766351.517      193748.446
#Sta/Elev= 30
       0  1581.6     9.9 1575.39    14.8 1571.38    44.5 1553.67   103.9 1510.99
   153.4 1479.62   183.1 1459.41     193 1453.22   212.8 1443.13   232.6 1429.31
   267.2 1408.52   282.1 1402.56   301.9  1396.9   336.7 1394.64   361.6 1389.71
   391.6 1389.17   397.7 1389.23   412.7 1389.57   426.5  1389.2   456.5 1392.43
   516.4 1423.36   536.1 1426.03   541.1 1427.93   565.8 1440.61   620.1 1456.79
   659.6 1471.51   694.2 1487.71   723.9 1503.46     793 1543.38   847.4 1575.84
#Mann= 3 , 0 , 0
       0      .1       0   397.7    .045       0   412.7      .1       0
Bank Sta=397.7,412.7
XS Rating Curve= 0 ,0
Exp/Cntr=0.3,0.1

Type RM Length L Ch R = 1 ,5056    ,410,405.4,400.9
XS GIS Cut Line= 3
     1765554.523      193471.867     1765882.801      193751.592
     1766198.093       194006.83
#Sta/Elev= 30
       0 1510.21    19.8 1500.16    34.7 1490.72    94.2 1465.51     119  1452.1
   143.8 1442.57   178.5 1436.87   218.1  1426.1     233 1424.05   257.8 1422.47
   292.5 1422.92   337.1 1416.05     347 1413.15   371.8 1391.12   381.7 1385.27
   387.5  1383.5   402.5  1383.2   406.5 1383.16   431.3 1388.15     461 1390.88
   500.6 1407.96   525.3 1409.46   535.2 1412.24   559.9 1426.98   574.8 1432.66
   624.2 1461.84   673.7  1488.4   728.1 1522.18   802.3 1565.85     837 1589.12
#Mann= 3 , 0 , 0
       0      .1       0   387.5    .045       0   402.5      .1       0
Bank Sta=387.5,402.5
XS Rating Curve= 0 ,0
Exp/Cntr=0.3,0.1

Type RM Length L Ch R = 1 ,4650.6  ,405.4,407.3,410.1
XS GIS Cut Line= 3
     1765265.087      193823.243     1765617.205      194033.244
     1765959.274      194258.209
#Sta/Elev= 30
       0  1565.2      10  1557.4      30 1544.35      65 1519.51     125 1475.66
     170  1448.4     180 1444.13     240  1425.3     250 1423.66     270 1422.66
     285 1418.77     330 1403.38     335 1400.88     355    1387     360 1384.93
     383  1382.4     398 1381.39     405 1381.27     415 1382.58     435 1388.97
   489.9  1392.2   514.8  1395.1   544.8 1401.82   574.8 1412.91   589.7 1414.62
   649.6 1448.38   699.6 1480.53   719.5 1490.27   754.5 1511.37   819.4 1545.94
#Mann= 3 , 0 , 0
       0      .1       0     383    .045       0     398      .1       0
Bank Sta=383,398
XS Rating Curve= 0 ,0
Exp/Cntr=0.3,0.1

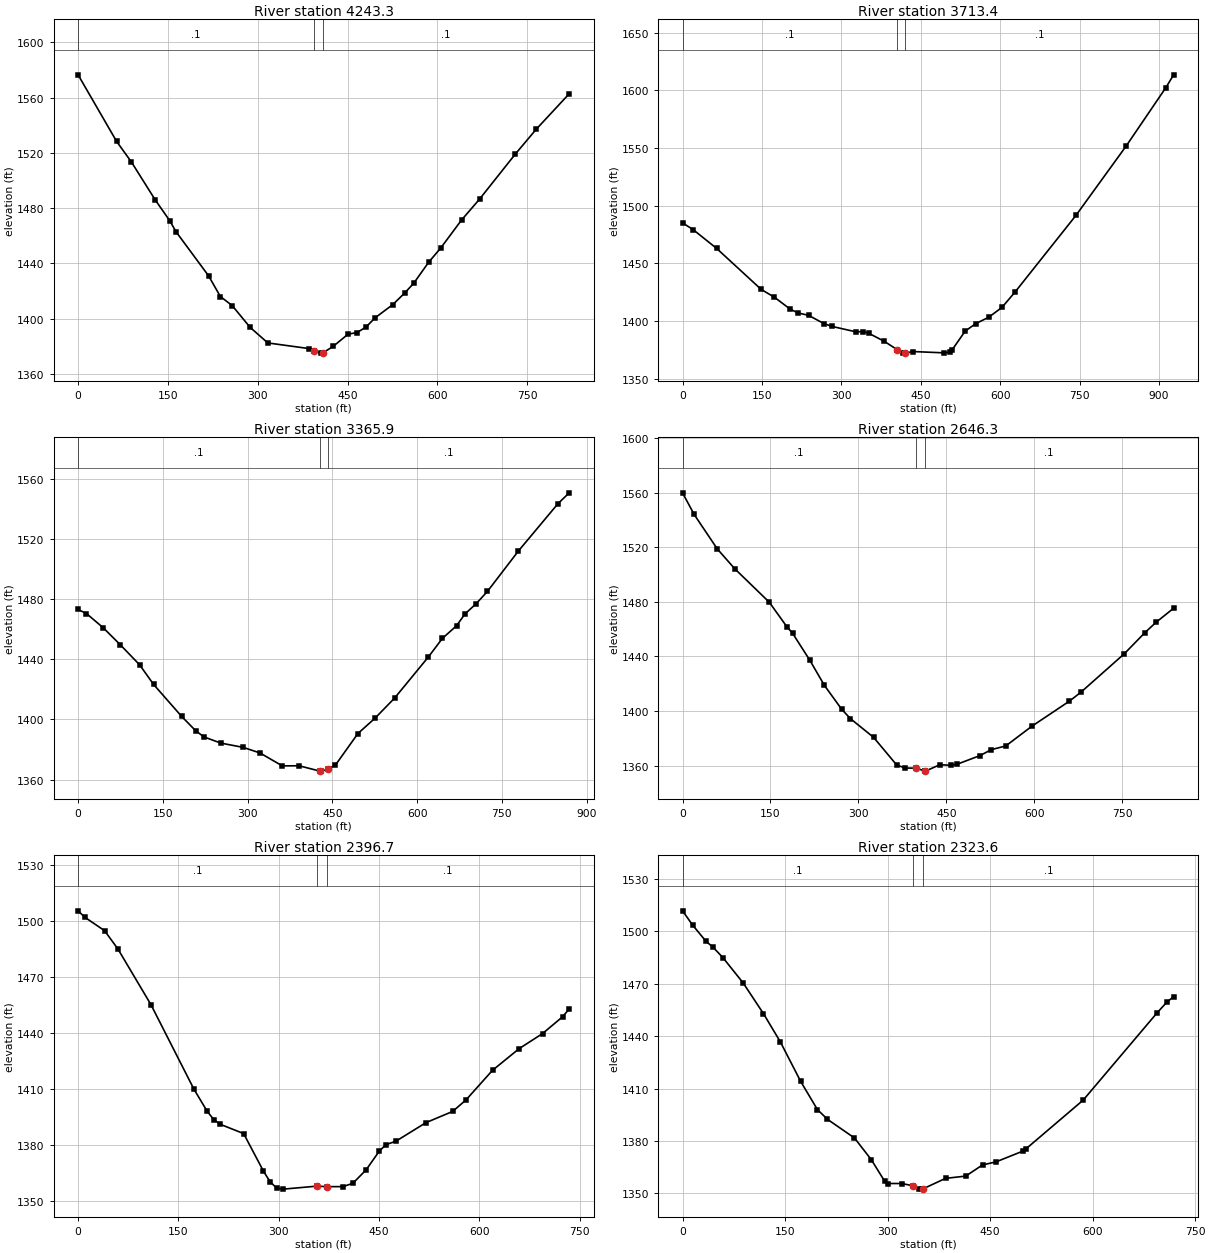
Type RM Length L Ch R = 1 ,4243.3  ,536.4,529.9,522.6
XS GIS Cut Line= 3
      1765090.98      194146.636     1765426.905      194383.146
     1765743.448      194642.566
#Sta/Elev= 30
       0 1576.46    64.4 1528.22    89.1 1513.34   128.7 1486.03   153.4 1470.68
   163.3 1463.06   217.8 1431.08   237.6 1416.05   257.4 1409.46   287.1 1393.81
   316.8 1382.47   386.1 1378.36   394.2  1376.9   405.9 1375.09   409.2 1375.41
   425.8 1379.92   450.8 1388.79   465.7 1389.99   480.7 1393.88   495.7 1400.56
   525.6 1410.22   545.6 1418.69   560.6 1425.72   585.5 1440.91   605.5  1451.1
   640.4 1471.44   670.4 1486.52   730.3 1519.21   765.2 1537.16   820.1 1562.75
#Mann= 3 , 0 , 0
       0      .1       0   394.2    .045       0   409.2      .1       0
Bank Sta=394.2,409.2
XS Rating Curve= 0 ,0
Exp/Cntr=0.3,0.1

Type RM Length L Ch R = 1 ,3713.4  ,346.5,347.5,347.7
XS GIS Cut Line= 4
     1764782.303      194578.746     1765033.261      194685.403
     1765312.451      194766.965     1765670.066      194835.978
#Sta/Elev= 30
       0 1485.12    19.8 1479.36    64.4 1462.98   148.7 1427.37   173.5 1420.67
   203.3 1410.32   218.2    1407     238 1404.95   267.7 1397.64   282.5 1395.32
   326.9 1390.68   341.7 1390.74   351.6 1389.42   381.1  1382.4   405.5 1375.16
   415.6 1372.18   420.5 1372.15   435.4 1373.52   494.5 1372.38   504.4 1373.04
   509.3 1374.99     534 1391.25   553.7 1397.69   578.5 1403.29   603.5 1411.82
   628.4 1425.26   743.2  1491.6     838 1551.72   912.8 1602.26   927.8 1613.56
#Mann= 3 , 0 , 0
       0      .1       0   405.5    .045       0   420.5      .1       0
Bank Sta=405.5,420.5
XS Rating Curve= 0 ,0
Exp/Cntr=0.3,0.1

Type RM Length L Ch R = 1 ,3365.9  ,732.5,719.6,727.9
XS GIS Cut Line= 3
     1764759.403      194904.678     1765212.463      195063.896
     1765582.545      195183.241
#Sta/Elev= 30
       0 1473.25    14.8 1470.55    44.6 1461.03    74.3  1449.9   108.9  1436.4
   133.7 1423.31   183.2 1402.07   207.9 1392.58   222.8 1388.38   252.5 1384.29
   292.1 1381.44   321.8 1377.73   361.4 1369.11   391.1 1369.18   427.4 1365.68
   430.7 1365.62   442.4 1367.04   455.5 1369.69   495.2 1390.66   525.1 1400.74
     560 1414.21   619.8 1441.59   644.7 1454.02   669.7  1462.4   684.6 1470.26
   704.6 1477.16   724.5 1485.35   779.3 1512.24   849.1 1543.66   869.1 1550.93
#Mann= 3 , 0 , 0
       0      .1       0   427.4    .045       0   442.4      .1       0
Bank Sta=427.4,442.4
XS Rating Curve= 0 ,0
Exp/Cntr=0.3,0.1

Type RM Length L Ch R = 1 ,2646.3  ,244.4,249.7,254.9
XS GIS Cut Line= 4
     1764506.385      195390.593      1764829.42      195550.392
     1764975.299       195648.92       1765262.4       195739.42
#Sta/Elev= 30
       0 1559.84    19.8    1544    59.2 1518.79    88.9 1504.28   148.1 1479.64
   177.7 1461.87   187.6 1457.02   217.2 1437.13   241.9 1418.81   271.5 1401.25
   286.3 1394.44   325.8 1380.74   365.3 1360.43     380 1358.25   397.8 1358.17
   412.8 1356.15   414.2 1355.99   438.6 1360.64   458.2 1360.29     468    1361
   507.1 1367.35   526.6 1371.72   551.2 1374.43   595.6 1388.83   659.8 1407.26
   679.5 1413.83   753.6 1442.05   788.1 1457.26   807.8  1465.1   837.5 1475.31
#Mann= 3 , 0 , 0
       0      .1       0   397.8    .045       0   412.8      .1       0
Bank Sta=397.8,412.8
XS Rating Curve= 0 ,0
Exp/Cntr=0.3,0.1

Type RM Length L Ch R = 1 ,2396.7  ,72.2,73.1,72.4
XS GIS Cut Line= 4
      1764532.18      195478.426     1764697.331      195725.264
     1764800.328      195838.916     1764995.668      196044.911
#Sta/Elev= 30
       0 1505.54     9.9 1502.12    39.6 1494.89    59.4 1485.15   108.9 1455.23
   173.2 1409.87     193 1398.02   202.9 1393.53   212.8 1390.99   247.5 1386.07
   277.2 1365.86   287.1 1360.19     297  1356.8   306.9 1356.26     357 1357.86
     372 1357.59     396  1357.6   410.8 1359.38   430.6 1366.57   450.4 1376.68
   460.3 1380.11   475.3 1381.98   520.1 1391.92   559.9 1397.91   579.9 1404.07
   619.7 1420.02   659.6 1431.65   694.4 1439.68   724.3 1448.68   734.3 1452.88
#Mann= 3 , 0 , 0
       0      .1       0     357    .045       0     372      .1       0
Bank Sta=357,372
XS Rating Curve= 0 ,0
Exp/Cntr=0.3,0.1

Type RM Length L Ch R = 1 ,2323.6  ,28.8,29.5,31.8
XS GIS Cut Line= 4
     1764478.906       195510.39     1764652.936      195767.883
     1764768.364      195902.846     1764921.084        196075.1
#Sta/Elev= 30
       0 1511.83    14.8 1503.64    34.5 1494.29    44.4 1491.09    59.2 1484.96
    88.8 1470.47   118.4 1452.95   143.1 1436.78   172.7 1414.23   197.3 1398.01
   212.1 1392.38   251.6  1381.7   276.3 1369.22     296 1356.78   300.9 1355.62
   320.6 1355.62   337.4 1354.32   345.3 1352.42   350.2  1352.4   352.4 1352.65
   384.8 1358.56   414.4 1359.87     439 1366.27   458.8 1368.03   498.2 1374.21
   503.1 1375.65   586.3 1403.41   694.1 1453.26   708.8 1459.59   718.6 1462.64
#Mann= 3 , 0 , 0
       0      .1       0   337.4    .045       0   352.4      .1       0
Bank Sta=337.4,352.4
XS Rating Curve= 0 ,0
Exp/Cntr=0.3,0.1