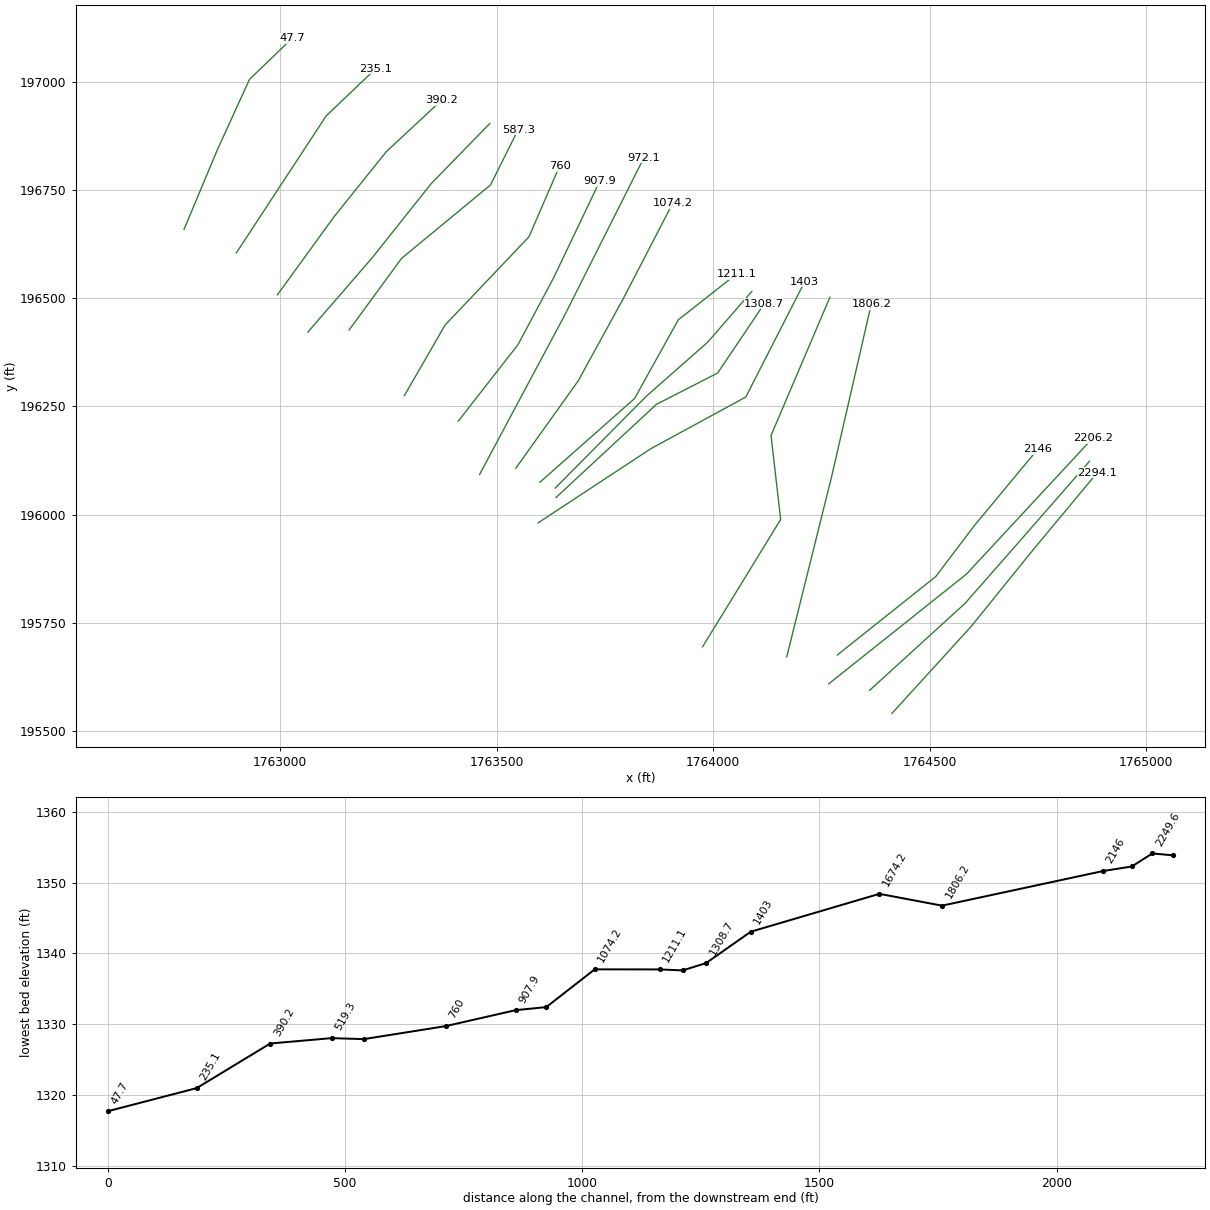
HEC-RAS study LtleHufCr.prj: LtleHufCr

--- LtleHufCr.g01 (geometry) --- (continued)

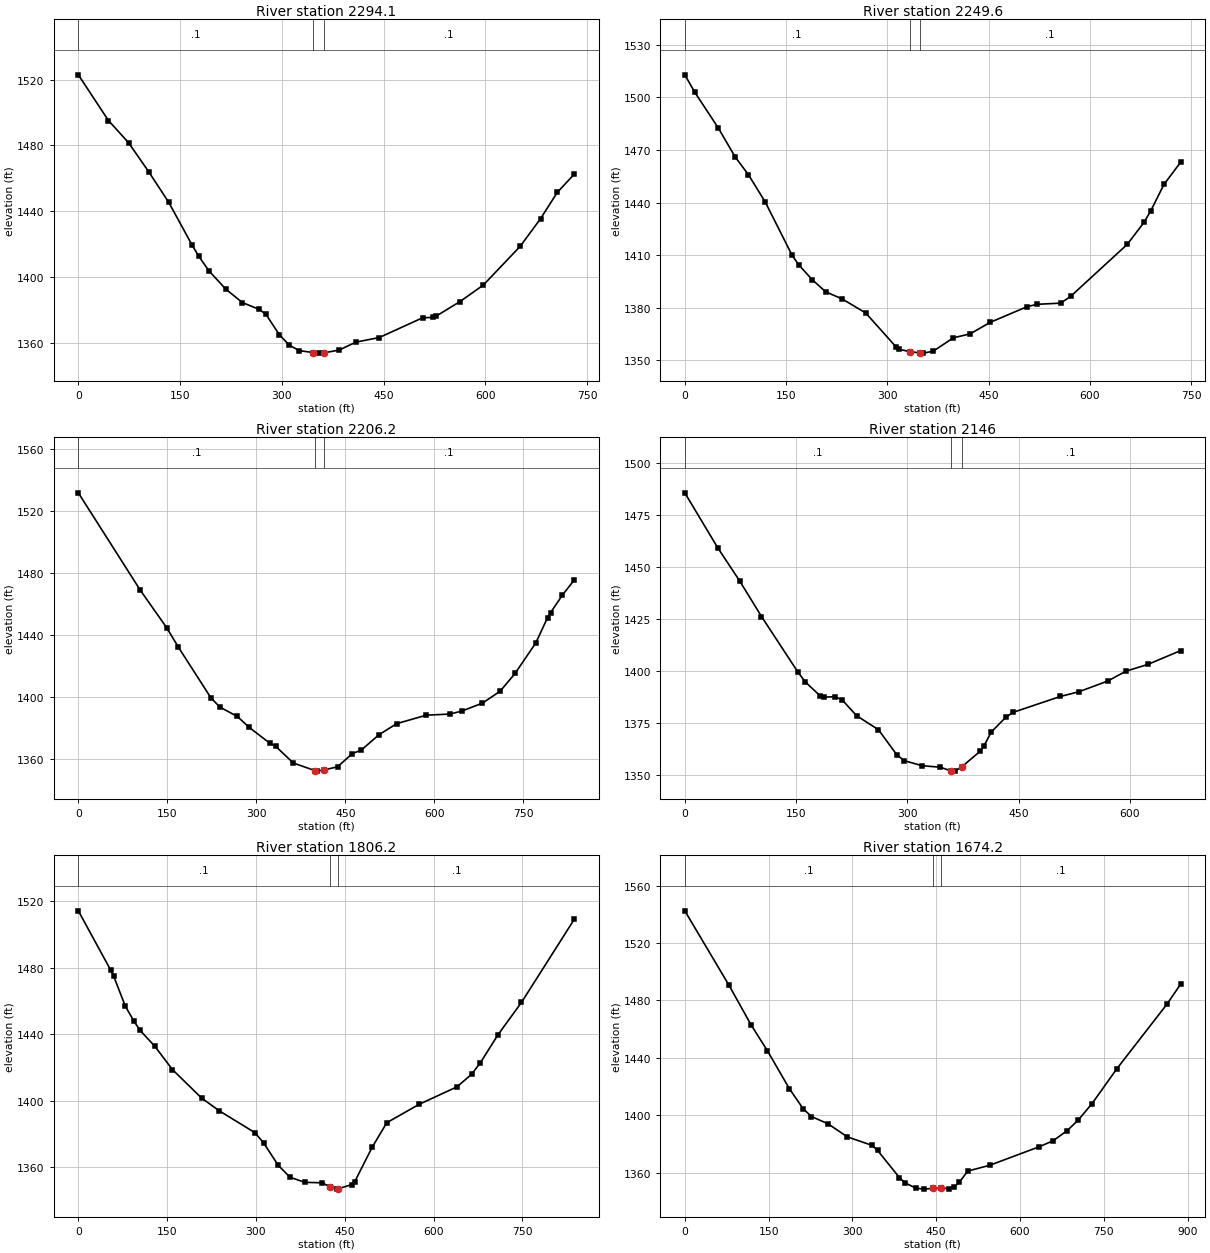
Type RM Length L Ch R = 1 ,2294.1  ,45.4,44.4,43.5
XS GIS Cut Line= 4
       1764413.2      195540.579      1764596.11      195741.246
     1764738.175      195917.052     1764887.343      196096.409
#Sta/Elev= 30
       0 1522.86    44.4 1495.12      74 1481.65   103.7 1464.04   133.3  1445.4
   167.8 1419.38   177.7 1412.57   192.5 1403.85   217.2 1392.77   241.9 1384.54
   266.6 1380.44   276.4  1377.5   296.1 1365.17   310.8 1358.71   325.6 1355.41
   346.6 1354.18     355 1353.87   361.6 1354.02   384.5 1355.74   409.1 1360.55
   443.5 1363.33   507.5 1375.34   522.4 1375.56   527.3 1376.32   562.1 1385.06
   596.8 1395.14   651.4 1418.79   681.2 1435.47     706 1451.51   730.8 1462.48
#Mann= 3 , 0 , 0
       0      .1       0   346.6    .045       0   361.6      .1       0
Bank Sta=346.6,361.6
XS Rating Curve= 0 ,0
Exp/Cntr=0.3,0.1

Type RM Length L Ch R = 1 ,2249.6  ,47.5,43.4,43
XS GIS Cut Line= 4
     1764361.702      195593.854     1764581.903      195794.521
     1764697.331      195925.931     1764869.585      196123.047
#Sta/Elev= 30
       0 1512.77    14.9 1502.78    49.6 1482.49    74.5 1466.05    94.3 1455.83
   119.2 1440.28   158.9 1409.98   168.8 1404.46   188.7 1396.06   208.5 1389.16
   233.4 1384.98   268.1 1377.03   312.9 1357.74   317.9 1356.29   333.2 1355.03
   348.2 1354.28   352.9 1354.15   367.9 1355.21   397.9 1362.88   422.8 1365.14
   452.8 1371.75   507.4 1380.67   522.2 1381.98   556.8 1382.64   571.6 1386.46
   655.6 1416.18   680.3 1428.65   690.2 1435.13   709.9 1450.29   734.6 1462.94
#Mann= 3 , 0 , 0
       0      .1       0   333.2    .045       0   348.2      .1       0
Bank Sta=333.2,348.2
XS Rating Curve= 0 ,0
Exp/Cntr=0.3,0.1

Type RM Length L Ch R = 1 ,2206.2  ,54.1,60.3,62.5
XS GIS Cut Line= 3
     1764266.835      195608.553     1764585.121      195862.098
     1764876.786      196176.168
#Sta/Elev= 30
       0 1531.54   104.2 1468.95   148.9 1444.66   168.7 1432.06   223.3 1399.58
   238.2 1393.62     268 1387.49   287.8 1380.51   322.6  1370.3   332.5  1368.3
   362.3 1357.53   399.4 1352.54     402  1352.3   414.4 1353.08   436.8  1355.1
   461.8 1363.62   476.7 1365.81   506.6 1375.75   536.5 1382.88   586.4 1388.35
   626.2 1389.05   646.2 1390.98     681  1396.1   710.9 1403.82   735.9 1415.19
   770.8 1434.83   790.7 1451.18   795.7 1454.33   815.6 1465.63   835.5 1475.32
#Mann= 3 , 0 , 0
       0      .1       0   399.4    .045       0   414.4      .1       0
Bank Sta=399.4,414.4
XS Rating Curve= 0 ,0
Exp/Cntr=0.3,0.1

Type RM Length L Ch R = 1 ,2146    ,330.9,339.7,349.2
XS GIS Cut Line= 4
     1764287.118      195675.541     1764514.422      195856.674
     1764603.213      195973.878     1764750.605       196151.46
#Sta/Elev= 30
       0 1485.64    44.3 1459.25    73.9 1443.26   103.4  1426.1   152.7 1399.24
   162.6 1394.57   182.3 1387.96   187.2 1387.27     202 1387.48   211.8 1386.11
   231.5 1378.38   261.1  1371.6   285.7  1359.6   295.6 1356.72   320.1 1354.25
   344.6 1353.55   358.3 1351.82   364.2 1351.66   373.3 1353.69   398.5 1361.32
   403.4 1363.81   413.2  1370.5   432.8 1377.59   442.6 1379.95   506.4 1387.61
     531 1389.83   570.3 1395.04   594.8 1399.79   624.3 1403.02   668.5 1409.69
#Mann= 3 , 0 , 0
       0      .1       0   358.3    .045       0   373.3      .1       0
Bank Sta=358.3,373.3
XS Rating Curve= 0 ,0
Exp/Cntr=0.3,0.1

Type RM Length L Ch R = 1 ,1806.2  ,124,132.1,139.7
XS GIS Cut Line= 3
     1764170.141      195671.143     1764274.476      196090.295
     1764365.351      196485.522
#Sta/Elev= 30
       0 1514.34    54.6 1478.65    59.6  1475.1    79.4 1456.89    94.3  1447.7
   104.3 1442.32   129.1 1432.84   158.9 1418.76   208.5 1401.51   238.3 1393.86
   297.9 1380.85   312.8 1374.71   337.6 1361.14   357.5 1353.93   382.3 1350.86
   412.1 1350.56   424.4 1348.22   436.9 1346.76   439.4 1347.02   461.6 1349.46
   466.6 1351.04   496.2  1371.9     521 1386.76   575.4 1397.78   639.7 1408.37
   664.4 1415.99   679.2 1422.91   708.9 1439.75   748.5 1459.18   837.5 1509.12
#Mann= 3 , 0 , 0
       0      .1       0   424.4    .045       0   439.4      .1       0
Bank Sta=424.4,439.4
XS Rating Curve= 0 ,0
Exp/Cntr=0.3,0.1

Type RM Length L Ch R = 1 ,1674.2  ,306.2,271.2,244.6
XS GIS Cut Line= 4
     1763975.739      195694.354     1764156.096      195988.473
     1764133.898      196182.703     1764269.859      196501.795
#Sta/Elev= 30
       0 1542.45    78.9 1490.69   118.3 1463.15   147.9 1444.87   187.3 1418.36
   211.9 1404.45   226.7 1399.05   256.3 1393.98   290.8  1384.9   335.2 1378.92
     345 1375.42   384.1 1356.49   393.9 1352.84   413.4 1349.16   428.1 1348.43
   444.3 1348.96   459.3 1349.21   472.1 1348.85   481.9 1349.88   491.6 1353.28
   506.3 1361.01   545.5 1365.02   634.6 1378.01   659.4 1382.19   684.2 1389.18
     704 1396.52   728.8 1408.03   773.4 1432.43   862.6 1477.19   887.4 1491.33
#Mann= 3 , 0 , 0
       0      .1       0   444.3    .045       0   459.3      .1       0
Bank Sta=444.3,459.3
XS Rating Curve= 0 ,0
Exp/Cntr=0.3,0.1

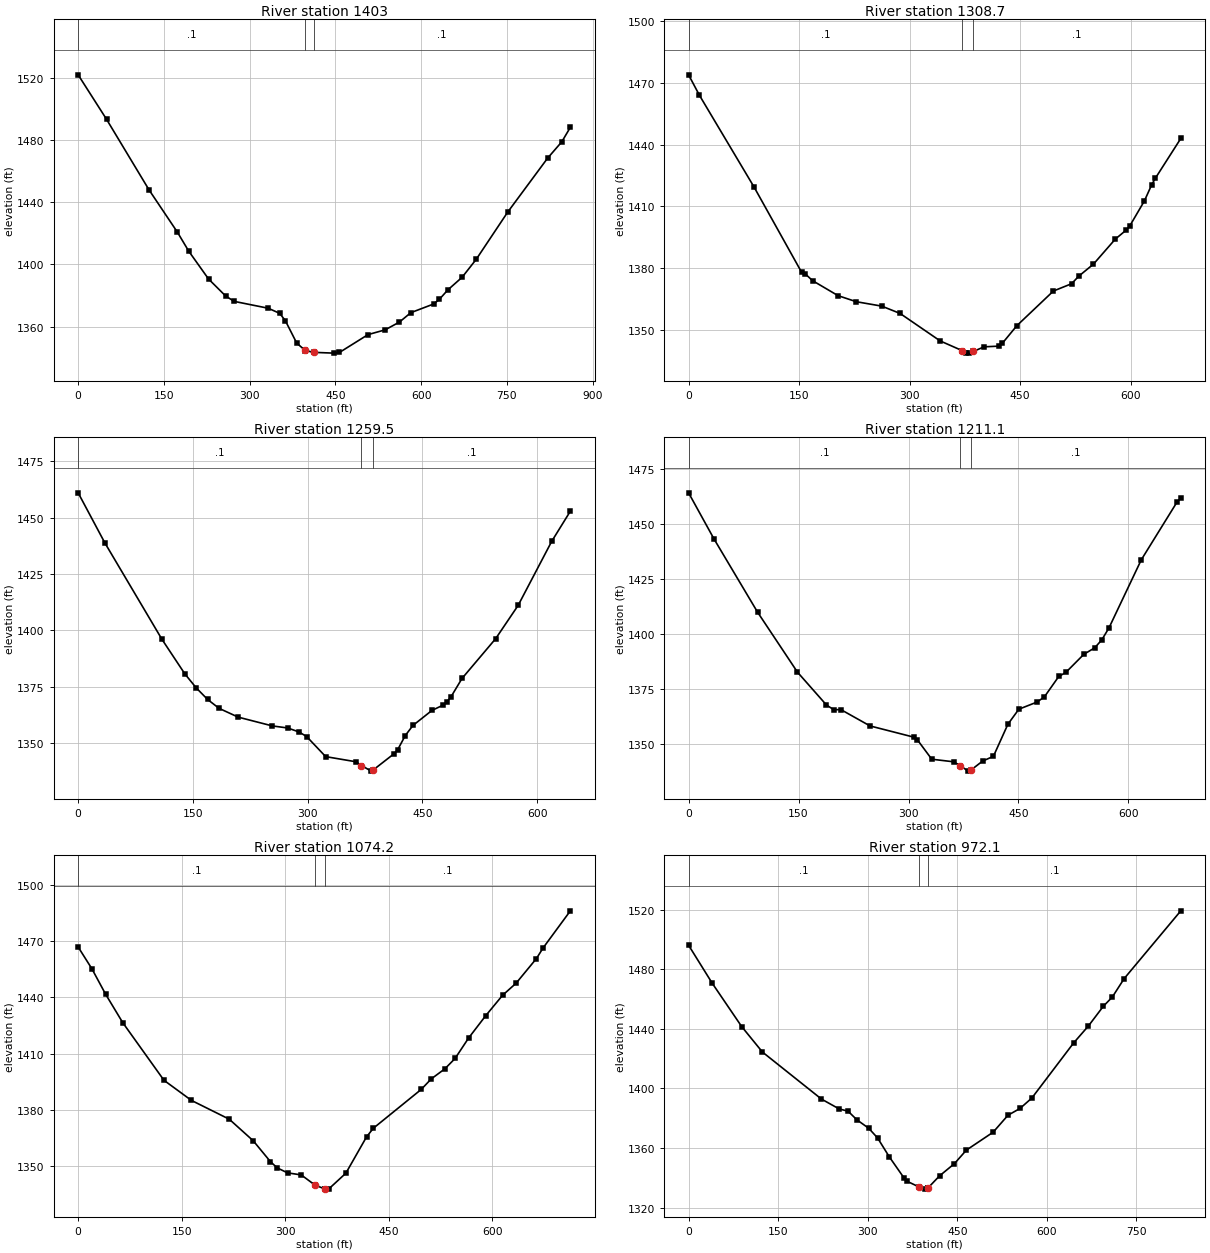
Type RM Length L Ch R = 1 ,1403    ,92.3,94.3,92.8
XS GIS Cut Line= 4
     1763595.426      195980.533     1763856.427      196152.181
     1764075.629      196271.494     1764211.612      196537.798
#Sta/Elev= 30
       0 1521.72    49.6 1493.21     124 1447.86   173.6 1420.72   193.4 1408.54
   228.1 1390.65   257.8 1379.81   272.7 1376.31   332.4 1371.89   352.3 1368.66
   362.3    1364   382.3 1349.53   397.2 1344.76   397.2 1344.75   412.2 1343.56
   447.2 1343.07   457.1 1343.51     507 1354.95     537 1358.02     562 1363.01
   581.9 1369.03   621.8 1374.61   631.7 1377.55   646.7 1383.67   671.6 1391.75
   696.5 1403.38   751.3 1433.55   821.1 1468.19     846 1478.73     861 1488.06
#Mann= 3 , 0 , 0
       0      .1       0   397.2    .045       0   412.2      .1       0
Bank Sta=397.2,412.2
XS Rating Curve= 0 ,0
Exp/Cntr=0.3,0.1

Type RM Length L Ch R = 1 ,1308.7  ,48.1,49.2,54.3
XS GIS Cut Line= 4
     1763636.866      196039.112     1763869.102       196254.52
     1764010.463      196326.883     1764118.167      196486.756
#Sta/Elev= 30
       0 1473.89    14.8  1463.9    89.1 1419.23   153.4 1377.96   158.4 1377.16
   168.3 1373.86   202.9 1366.57   227.7 1363.62   262.3 1361.47   287.1 1357.93
   341.6 1344.56   371.6 1339.82   376.3 1338.69   381.3 1338.63   386.6 1339.43
   401.1 1341.69     421 1342.02   425.9 1343.37   445.8    1352   495.3 1368.81
     520 1372.36   529.9 1376.08   549.7 1381.88   579.4 1394.06   594.2 1398.44
   599.1  1400.5   618.9 1412.63   628.8 1420.49   633.7  1423.6   668.3 1442.97
#Mann= 3 , 0 , 0
       0      .1       0   371.6    .045       0   386.6      .1       0
Bank Sta=371.6,386.6
XS Rating Curve= 0 ,0
Exp/Cntr=0.3,0.1

Type RM Length L Ch R = 1 ,1259.5  ,40.9,48.5,55.7
XS GIS Cut Line= 4
     1763635.183      196060.989     1763845.542      196273.031
     1763986.903      196397.564     1764089.558      196515.365
#Sta/Elev= 30
       0 1461.02    34.8 1438.88   109.5 1396.06   139.4 1380.75   154.3 1374.52
   169.2 1369.38   184.2 1365.44   209.1 1361.55   253.9 1357.64   273.8 1356.74
   288.7 1354.97   298.7 1352.91   323.5 1344.03   363.1 1341.75   370.3 1340.09
     383  1337.6   385.3 1338.03   412.7 1345.27   417.7 1347.17   427.6  1353.4
   437.5 1357.84   462.3  1364.5   477.2 1366.92   482.1 1368.42   487.1 1370.44
   501.7 1378.71   545.7 1396.36     575 1411.08   618.9  1439.5   643.3 1452.89
#Mann= 3 , 0 , 0
       0      .1       0   370.3    .045       0   385.3      .1       0
Bank Sta=370.3,385.3
XS Rating Curve= 0 ,0
Exp/Cntr=0.3,0.1

Type RM Length L Ch R = 1 ,1211.1  ,136.4,136.9,137.3
XS GIS Cut Line= 4
     1763599.842      196074.452     1763818.616      196267.982
     1763919.588      196449.733     1764054.218      196555.754
#Sta/Elev= 30
       0 1464.34    34.6  1443.4    94.1 1410.05   148.5 1382.77   188.1  1367.8
     198  1365.7   207.9  1365.7   247.5  1358.3   306.9 1353.22   311.9 1352.05
   331.7 1343.16   361.4 1341.99   370.7 1340.22   381.2 1337.74   385.7 1338.36
     401  1342.3   415.8 1344.48   435.6  1359.1   450.5 1365.91   475.2 1369.15
   485.2 1371.46   504.9 1380.79   514.7 1382.68   539.2  1390.9   553.9 1393.81
   563.6 1397.44   573.4 1402.88   617.5 1433.88   666.5 1460.28   671.4 1462.02
#Mann= 3 , 0 , 0
       0      .1       0   370.7    .045       0   385.7      .1       0
Bank Sta=370.7,385.7
XS Rating Curve= 0 ,0
Exp/Cntr=0.3,0.1

Type RM Length L Ch R = 1 ,1074.2  ,101.7,102.1,102.4
XS GIS Cut Line= 4
      1763543.94      196106.585     1763688.561      196309.055
     1763793.741      196501.008     1763906.809      196719.255
#Sta/Elev= 30
       0 1466.91    19.9 1455.31    39.8 1441.73    64.7 1426.53   124.4 1395.81
   164.2 1385.08     219 1375.06   253.8 1363.54   278.7 1352.42   288.6 1349.08
   303.5 1346.43   323.4 1345.33   343.4 1339.88   358.3 1337.75   358.4 1337.75
   363.2 1337.82   388.1 1346.26     418  1365.6   427.9 1370.23   497.2 1390.91
   511.9 1396.57   531.6 1401.93   546.4 1407.46     566 1418.37   590.6 1430.18
   615.2 1441.15   634.8 1447.59   664.3 1460.75   674.2 1466.54   713.5 1486.21
#Mann= 3 , 0 , 0
       0      .1       0   343.4    .045       0   358.4      .1       0
Bank Sta=343.4,358.4
XS Rating Curve= 0 ,0
Exp/Cntr=0.3,0.1

Type RM Length L Ch R = 1 ,972.1   ,64.6,64.2,63.9
XS GIS Cut Line= 3
     1763460.523       196092.37     1763656.196      196458.636
     1763839.913      196823.942
#Sta/Elev= 30
       0 1496.05    39.6 1470.54      89 1441.43   123.6 1424.41   222.5 1392.83
   252.1 1386.23     267 1384.71   281.8 1378.94   301.6 1373.25   316.4 1366.79
   336.2    1354   360.9 1339.81   365.8 1337.69   385.4 1333.95   395.5 1332.41
   400.4    1333   400.4 1333.01   420.2 1341.29   445.2 1349.54   465.1 1358.57
     510 1370.62   534.9 1382.02   554.9 1386.52   574.8 1393.54   644.6 1430.43
   669.6 1441.93   694.5 1455.12   709.5 1461.28   729.4 1473.69   824.2 1519.14
#Mann= 3 , 0 , 0
       0      .1       0   385.4    .045       0   400.4      .1       0
Bank Sta=385.4,400.4
XS Rating Curve= 0 ,0
Exp/Cntr=0.3,0.1

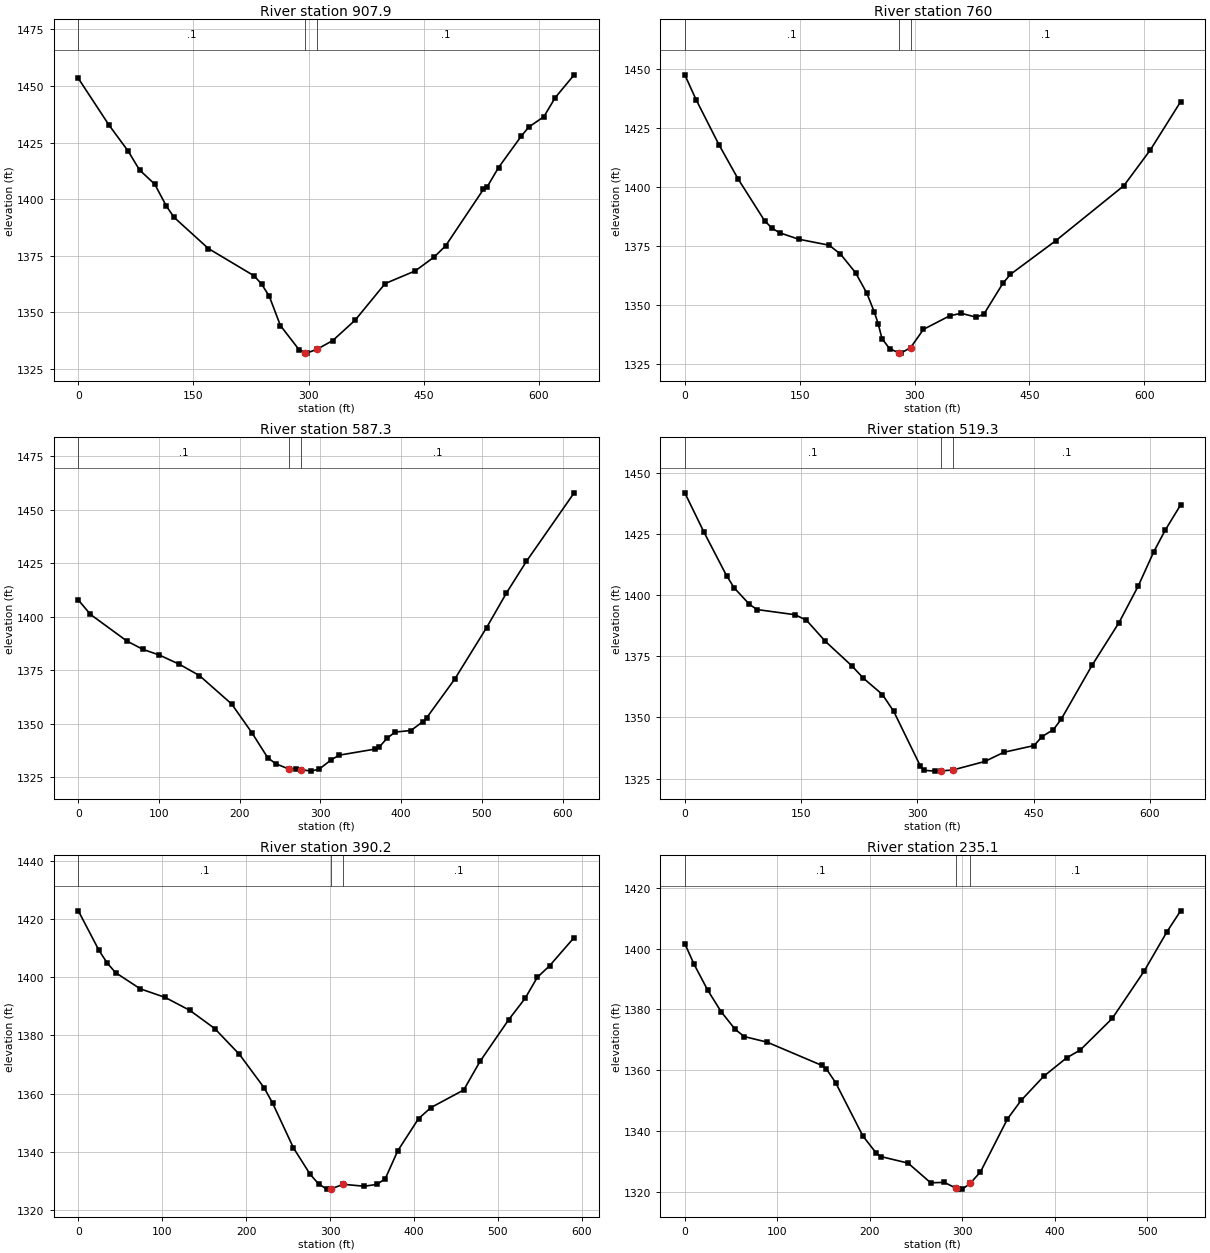
Type RM Length L Ch R = 1 ,907.9   ,153.8,147.8,141.9
XS GIS Cut Line= 4
     1763411.361      196215.813     1763549.356      196392.515
     1763631.817      196547.339     1763737.838      196769.478
#Sta/Elev= 30
       0 1453.37    39.9 1432.76    64.8 1421.28    79.7 1412.92    99.6 1406.58
   114.6 1396.98   124.6    1392   169.4 1378.19   229.1  1366.1   238.8 1362.42
   248.6 1357.18   263.2 1344.16   287.6 1333.45   295.7 1332.06   297.3 1331.98
   310.7 1333.66   331.4 1337.54   360.6 1346.57   399.6 1362.72     439 1368.34
   463.6 1374.49   478.4  1379.4   527.6 1404.33   532.5 1405.45   547.3 1413.97
   576.8 1427.81   586.7 1431.86   606.4 1436.46   621.1 1444.84   645.8 1454.94
#Mann= 3 , 0 , 0
       0      .1       0   295.7    .045       0   310.7      .1       0
Bank Sta=295.7,310.7
XS Rating Curve= 0 ,0
Exp/Cntr=0.3,0.1

Type RM Length L Ch R = 1 ,760     ,175.6,172.8,170.1
XS GIS Cut Line= 4
     1763286.828      196274.714     1763380.911        196437.9
       1763574.6       196641.58      1763645.28      196804.819
#Sta/Elev= 30
       0 1447.63    14.9    1437    44.6 1418.02    69.4 1403.61   104.1 1385.85
     114  1382.6   123.9 1380.71   148.7 1377.98   188.4 1375.45   203.2  1371.7
   222.9  1363.8   237.7 1355.08   247.5 1347.04   252.5 1342.13   257.4 1335.88
   267.3 1331.64   279.8 1329.78   282.1 1329.72   294.8 1332.06   311.6  1339.8
   346.2 1345.59     361 1346.58   380.7 1344.94   390.5 1346.25   415.2 1359.26
   425.1 1363.09   484.3 1377.35   573.2 1400.66   607.8 1415.82   647.3 1436.24
#Mann= 3 , 0 , 0
       0      .1       0   279.8    .045       0   294.8      .1       0
Bank Sta=279.8,294.8
XS Rating Curve= 0 ,0
Exp/Cntr=0.3,0.1

Type RM Length L Ch R = 1 ,587.3   ,63.3,67.9,72.6
XS GIS Cut Line= 4
     1763159.244      196426.419     1763280.358      196591.814
     1763485.721      196761.311      1763549.67      196889.209
#Sta/Elev= 30
       0 1407.78      15 1401.07      60 1388.66      80 1384.73     100 1382.14
     125 1377.81     150 1372.51     190  1359.2   214.9 1345.87   234.6 1334.17
   244.4 1331.37   260.7 1328.87   269.1  1329.1   275.7 1328.57   288.8 1327.88
   298.7  1328.9   313.5 1333.21   323.3 1335.34   367.7 1338.18   372.6 1339.04
   382.5 1343.23   392.4 1346.11   412.1 1346.85   426.9 1350.98   431.8 1352.91
   466.3 1370.82   505.8 1394.88   530.4 1411.05   555.1 1425.81   614.3 1457.83
#Mann= 3 , 0 , 0
       0      .1       0   260.7    .045       0   275.7      .1       0
Bank Sta=260.7,275.7
XS Rating Curve= 0 ,0
Exp/Cntr=0.3,0.1

Type RM Length L Ch R = 1 ,519.3   ,129.1,129.2,129.3
XS GIS Cut Line= 4
     1763063.857      196421.497     1763211.533      196592.027
      1763348.66      196764.315      1763484.03      196903.201
#Sta/Elev= 30
       0 1441.81    24.5 1425.87    53.9 1407.93    63.8 1402.92    83.4 1396.22
    93.2 1394.08   142.2 1391.97   156.9 1389.74   181.4 1381.07   215.8 1370.98
   230.5 1365.98     255 1359.33   269.6 1352.42   303.9 1330.11   308.8 1328.34
   323.4 1328.02     331 1328.11     346  1328.5   387.1 1331.97   411.5 1335.71
   450.8 1338.49   460.7  1342.1   475.6    1345   485.6 1349.23   525.4 1371.28
   560.2 1388.74     585  1403.7   604.9 1417.59   619.8 1426.54   639.7 1436.87
#Mann= 3 , 0 , 0
       0      .1       0     331    .045       0     346      .1       0
Bank Sta=331,346
XS Rating Curve= 0 ,0
Exp/Cntr=0.3,0.1

Type RM Length L Ch R = 1 ,390.2   ,152.9,155.1,157.2
XS GIS Cut Line= 4
     1762993.535      196507.641      1763123.63      196686.961
     1763244.935      196838.153     1763373.273        196957.7
#Sta/Elev= 30
       0 1422.78    24.6  1409.2    34.5 1404.83    44.3 1401.58    73.8 1396.01
   103.4 1393.07   132.9 1388.61   162.5 1382.38     192 1373.49   221.5    1362
   231.5 1356.77   256.3 1341.42   276.2 1332.36   286.2 1329.07   296.1 1327.26
   300.8 1327.34   315.8 1328.91   340.8 1328.25   355.7 1328.88   365.7 1330.82
   380.6 1340.41   405.4 1351.47   420.2 1355.26   459.2 1361.29   478.7 1371.13
   512.8 1385.42   532.3 1392.72   546.9 1399.95   561.5 1403.91   590.8 1413.62
#Mann= 3 , 0 , 0
       0      .1       0   300.8    .045       0   315.8      .1       0
Bank Sta=300.8,315.8
XS Rating Curve= 0 ,0
Exp/Cntr=0.3,0.1

Type RM Length L Ch R = 1 ,235.1   ,183.8,187.4,194.2
XS GIS Cut Line= 4
     1762898.601      196604.333     1762998.809      196757.283
      1763106.05      196920.781     1763220.323       197029.78
#Sta/Elev= 30
       0 1401.64     9.9 1394.92    24.7 1386.36    39.5 1379.17    54.4 1373.49
    64.2 1371.09      89 1369.25   148.3  1361.6   153.2 1360.42   163.1 1355.95
   192.6 1338.43   207.3 1332.69   212.2 1331.64   241.5  1329.5     266 1323.02
   280.6 1323.18   293.7 1321.21   295.3 1320.95   300.2 1320.95   308.7 1322.84
   319.7 1326.56     349 1344.01   363.7 1350.08   388.2 1358.02   412.9 1364.07
   427.7 1366.66   462.3 1377.03   496.8 1392.56   521.5 1405.51   536.3  1412.4
#Mann= 3 , 0 , 0
       0      .1       0   293.7    .045       0   308.7      .1       0
Bank Sta=293.7,308.7
XS Rating Curve= 0 ,0
Exp/Cntr=0.3,0.1

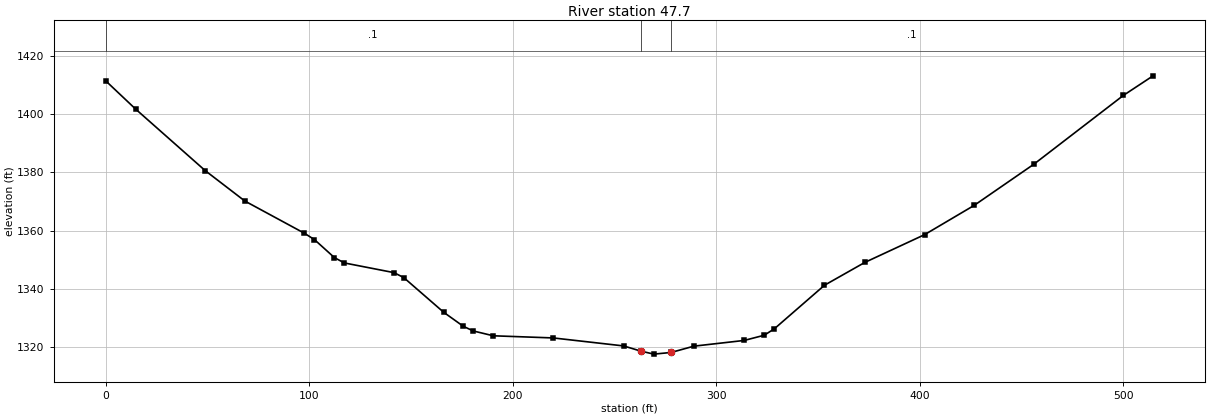
Type RM Length L Ch R = 1 ,47.7    ,75.6,47.7,16.5
XS GIS Cut Line= 4
     1762777.735      196658.833     1762855.089      196843.427
     1762928.927      197005.168     1763027.377      197100.102
#Sta/Elev= 30
       0 1411.34    14.6 1401.72    48.8 1380.62    68.3 1370.18    97.6 1359.12
   102.5 1356.96   112.3 1350.79   117.2 1348.95   141.6 1345.63   146.4 1343.93
     166 1332.05   175.7 1327.21   180.6 1325.62   190.4 1323.97   219.9 1323.23
   254.5 1320.49   262.8 1318.74   269.3 1317.68   277.8 1318.25     289 1320.41
   313.7 1322.37   323.6 1324.16   328.6 1326.39   353.2  1341.3     373 1349.12
   402.4 1358.65   426.8  1368.7   456.1  1382.8   500.1  1406.4   514.7 1413.12
#Mann= 3 , 0 , 0
       0      .1       0   262.8    .045       0   277.8      .1       0
Bank Sta=262.8,277.8
XS Rating Curve= 0 ,0
Exp/Cntr=0.3,0.1

Chan Stop Cuts=-1
Use User Specified Reach Order=0